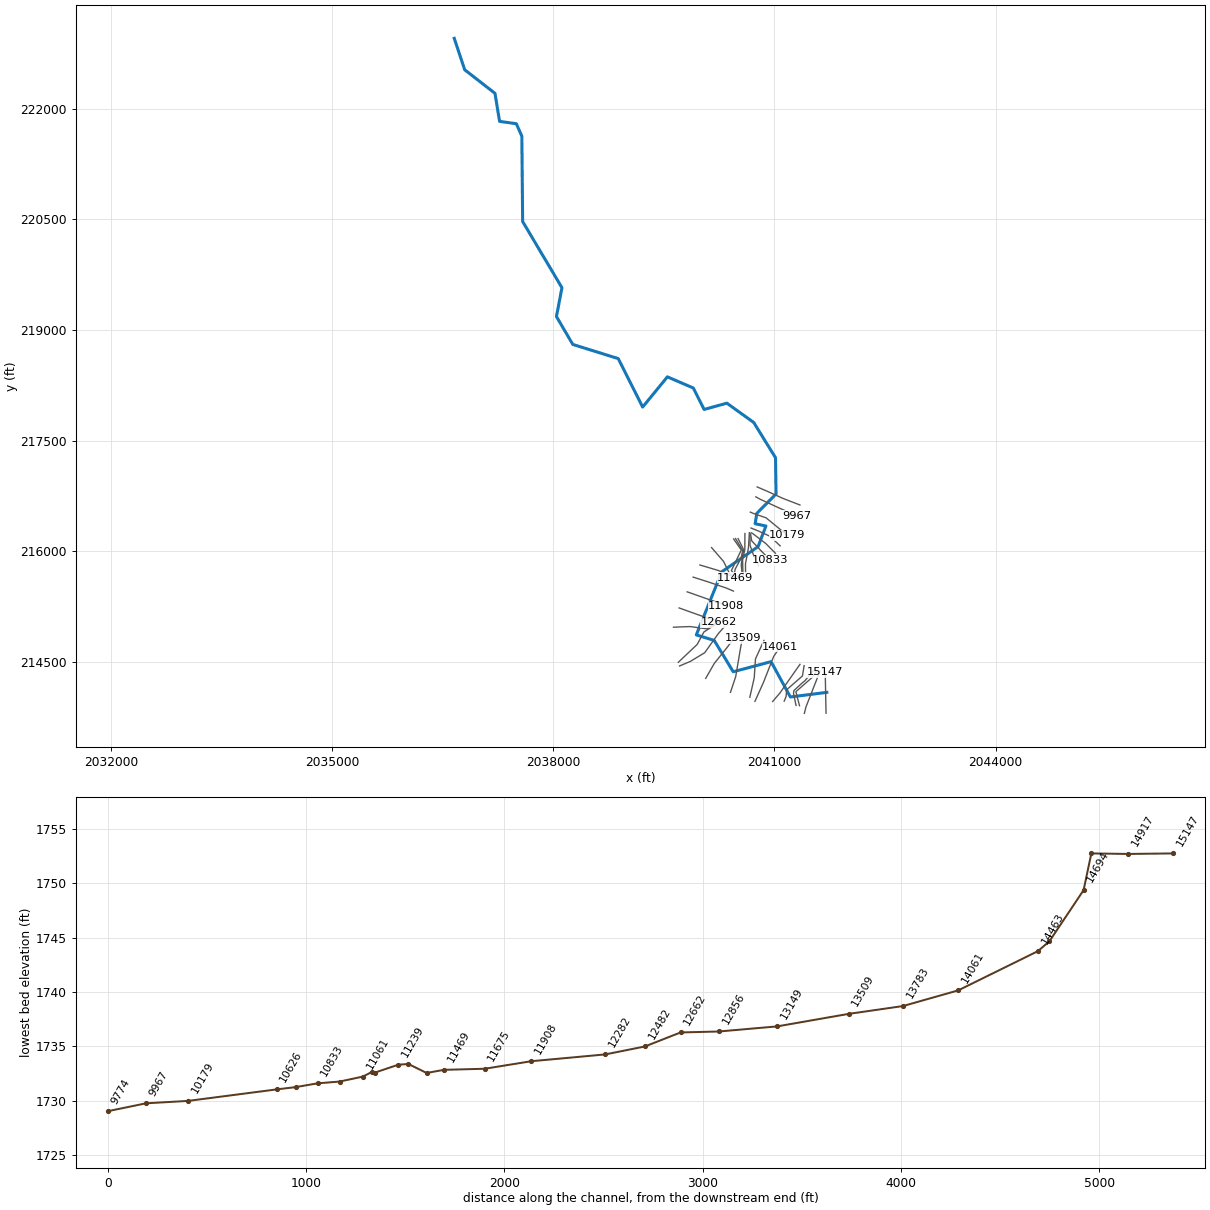
--- LTLSTNYCK.prj (project) ---

Proj Title=LTLSTNYCK
Current Plan=p01
Default Exp/Contr=0,0
English Units
Geom File=g01
Flow File=f01
Plan File=p01
Background Map Layer=QC
BEGIN DESCRIPTION:
Stream Name: Little Stony Creek
Flood Zone: Approximate
Summers County, West Virginia
HEC-RAS Version: 5.0.7
Hydrology Method:
Regression.
Model Notes:
END DESCRIPTION:
DSS Export Rating Curves= 0
DSS Export Rating Curve Sorted= 0
DSS Export Volume Flow Curves= 0
DXF OffsetX= 0
DXF OffsetY= 0
DXF ScaleX= 0
DXF ScaleY= 0

--- LTLSTNYCK.p01 (plan) ---

Plan Title=Floodplain
Program Version=5.07
Short Identifier=Floodplain
Geom File=g01
Flow File=f01
Subcritical Flow
K Sum by GR= 0
Std Step Tol= 0.01
Critical Tol= 0.01
Num of Std Step Trials= 20
Max Error Tol= 0.3
Flow Tol Ratio= 0.001
Split Flow NTrial= 30
Split Flow Tol= 0.02
Split Flow Ratio= 0.02
Log Output Level= 0
Friction Slope Method= 1
Unsteady Friction Slope Method= 2
Unsteady Bridges Friction Slope Method= 1
Parabolic Critical Depth
Global Vel Dist= 0 , 0 , 0
Global Log Level= 0
CheckData=True
Encroach Param=-1 ,0,0, 0
Mapping Interval=1HOUR
Computation Time Step Use Courant=        0
Computation Time Step Use Time Series=    0
Computation Time Step Count To Double=0
Computation Time Step Max Doubling=0
Computation Time Step Max Halving=0
Computation Time Step Residence Courant=0
Run HTab= 0
Run UNet= 0
Run Sediment= 0
Run PostProcess= 0
Run WQNet= 0
Run RASMapper=-1
UNET Theta= 0
UNET Theta Warmup= 0
UNET ZTol= 0
UNET ZSATol= 0
UNET MxIter= 0
UNET Max Iter WO Improvement= 0
UNET MaxInSteps= 0
UNET DtIC= 0
UNET DtMin= 0
UNET MaxCRTS= 0
UNET WFStab= 0
UNET SFStab= 0
UNET WFX= 1
UNET SFX= 1
UNET 1D Methodology=Finite Difference
UNET DSS MLevel= 1
UNET Pardiso=0
UNET DZMax Abort= 0
UNET Use Existing IB Tables= 0
UNET Froude Reduction=False
UNET Froude Limit= 0
UNET Froude Power= 0
UNET D1 Cores= 0
UNET D2 Coriolis=0
UNET D2 Cores= 0
UNET D2 Theta= 1
UNET D2 Theta Warmup= 1
UNET D2 Z Tol= 0.01
UNET D2 Volume Tol= 0.01
UNET D2 Max Iterations= 20
UNET D2 Equation= 0
UNET D2 RampUpFraction=0.1
UNET D2 TimeSlices= 1
UNET D2 BCVolumeCheck=0
UNET D1D2 MaxIter= 0
UNET D1D2 ZTol=0.01
UNET D1D2 QTol=0.1
UNET D1D2 MinQTol=1
Write IC File= 0
Write IC File at Fixed DateTime=0
Write IC File at Sim End=0
Echo Input=False
Echo Parameters=False
Echo Output=False
Write Detailed= 0
HDF Write Warmup=0
HDF Write Time Slices=0
HDF Flush=0
HDF Face Node Velocities=0
HDF Compression= 1
HDF Chunk Size= 1
HDF Spatial Parts= 1
HDF Use Max Rows=0
HDF Fixed Rows= 1
Calibration Method= 0
Calibration Iterations= 20
Calibration Max Change=0.05
Calibration Tolerance=0.2
Calibration Maximum=1.5
Calibration Minimum=0.5
Calibration Optimization Method= 1
WQ AD Non Conservative
WQ ULTIMATE=-1
WQ Max Comp Step=1HOUR
WQ Output Interval=15MIN
WQ Output Selected Increments= 0
WQ Output face flow=0
WQ Output face velocity=0
WQ Output face area=0
WQ Output face dispersion=0
WQ Output cell volume=0
WQ Output cell surface area=0
WQ Output cell continuity=0
WQ Output cumulative cell continuity=0
WQ Output face conc=0
WQ Output face dconc_dx=0
WQ Output face courant=0
WQ Output face peclet=0
WQ Output face adv mass=0
WQ Output face disp mass=0
WQ Output cell mass=0
WQ Output cell source sink temp=0
WQ Output nsm pathways=0
WQ Output nsm derived pathways=0
WQ Output MaxMinRange=-1
WQ Daily Max Min Mean=-1
WQ Daily Range=0
WQ Daily Time=0
WQ Create Restart=0
WQ Fixed Restart=0
WQ System Summary=0
WQ Write To DSS=0
WQ Use Fixed Temperature=0
Sorting and Armoring Iterations= 10
XS Update Threshold= 0.02
Bed Roughness Predictor= 0
Hydraulics Update Threshold= 0.02
Energy Slope Method= 1
Volume Change Method= 1
Sediment Retention Method= 0
XS Weighting Method= 0
Number of US Weighted Cross Sections= 1
Number of DS Weighted Cross Sections= 1
Upstream XS Weight=0
Main XS Weight=1
Downstream XS Weight=0
Number of DS XS's Weighted with US Boundary= 1
Upstream Boundary Weight= 1
Weight of XSs Associated with US Boundary= 0
Number of US XS's Weighted with DS Boundary= 1
Downstream Boundary Weight= 0.5
Weight of XSs Associated with DS Boundary= 0.5
Percentile Method= 0
Sediment Output Level= 3
Mass or Volume Output= 0
Output Increment Type= 1
Profile and TS Output Increment= 1
XS Output Flag= 0
XS Output Increment= 10
Write Gradation File= 0
Read Gradation Hotstart= 0
Write HDF5 File= 1
Write Binary Output= 1
Write DSS Sediment File= 0
SV Curve= 0
Specific Gage Flag= 0

--- LTLSTNYCK.f01 (steady flow) ---

Flow Title=Flows
Program Version=5.07
Number of Profiles= 6
Profile Names=01pct,10pct,04pct,02pct,0_2pct,01plus
River Rch & RM=LTLSTNYCK,Main            ,15147
     759     405     536     644    1054    1122
River Rch & RM=LTLSTNYCK,Main            ,12662
     960     517     681     816    1327    1419
River Rch & RM=LTLSTNYCK,Main            ,7101
    1075     582     765     915    1483    1589
Boundary for River Rch & Prof#=LTLSTNYCK,Main            , 1
Up Type= 0
Dn Type= 3
Dn Slope=0.0164
Boundary for River Rch & Prof#=LTLSTNYCK,Main            , 2
Up Type= 0
Dn Type= 3
Dn Slope=0.0164
Boundary for River Rch & Prof#=LTLSTNYCK,Main            , 3
Up Type= 0
Dn Type= 3
Dn Slope=0.0164
Boundary for River Rch & Prof#=LTLSTNYCK,Main            , 4
Up Type= 0
Dn Type= 3
Dn Slope=0.0164
Boundary for River Rch & Prof#=LTLSTNYCK,Main            , 5
Up Type= 0
Dn Type= 3
Dn Slope=0.0164
Boundary for River Rch & Prof#=LTLSTNYCK,Main            , 6
Up Type= 0
Dn Type= 3
Dn Slope=0.0164
DSS Import GetInterval= 0
DSS Import GetPeak= 0
DSS Import FillOption= 0

--- LTLSTNYCK.g01 (geometry) ---

Geom Title=Geometry
Program Version=5.07

River Reach=LTLSTNYCK       ,Main
Reach XY= 30
2041710.33607031214082.467734374     2041215.738214019.501000038
     2040953.586214498.6679999862040440.77500002214361.699000052
2040182.75200004214786.8620000192039939.89100002214862.486000014
     2040285.847215718.730999983     2040777.537216059.623000038
     2040883.981216339.419999999     2040737.939216370.848000001
2040760.39000001216511.6529999882041021.27200001 216774.32000001
     2041014.328217265.9870000112040719.18900002217744.459000041
     2040354.606218006.959000029     2040045.578217921.542000051
2039899.35900002218212.771000016     2039547.619 218364.31500003
2039212.24400001217954.1810000322038881.29800001218612.060000033
2038265.10900001218803.9080000392038043.14700001219182.480000028
2038117.80000001219573.972999991     2037584.814220471.976000033
2037573.81000001221630.395999993     2037499.157221799.667000001
2037271.72599999221831.7850000062037209.38800002222212.076000022
     2036798.408 222532.53399999     2036656.922222958.463000019

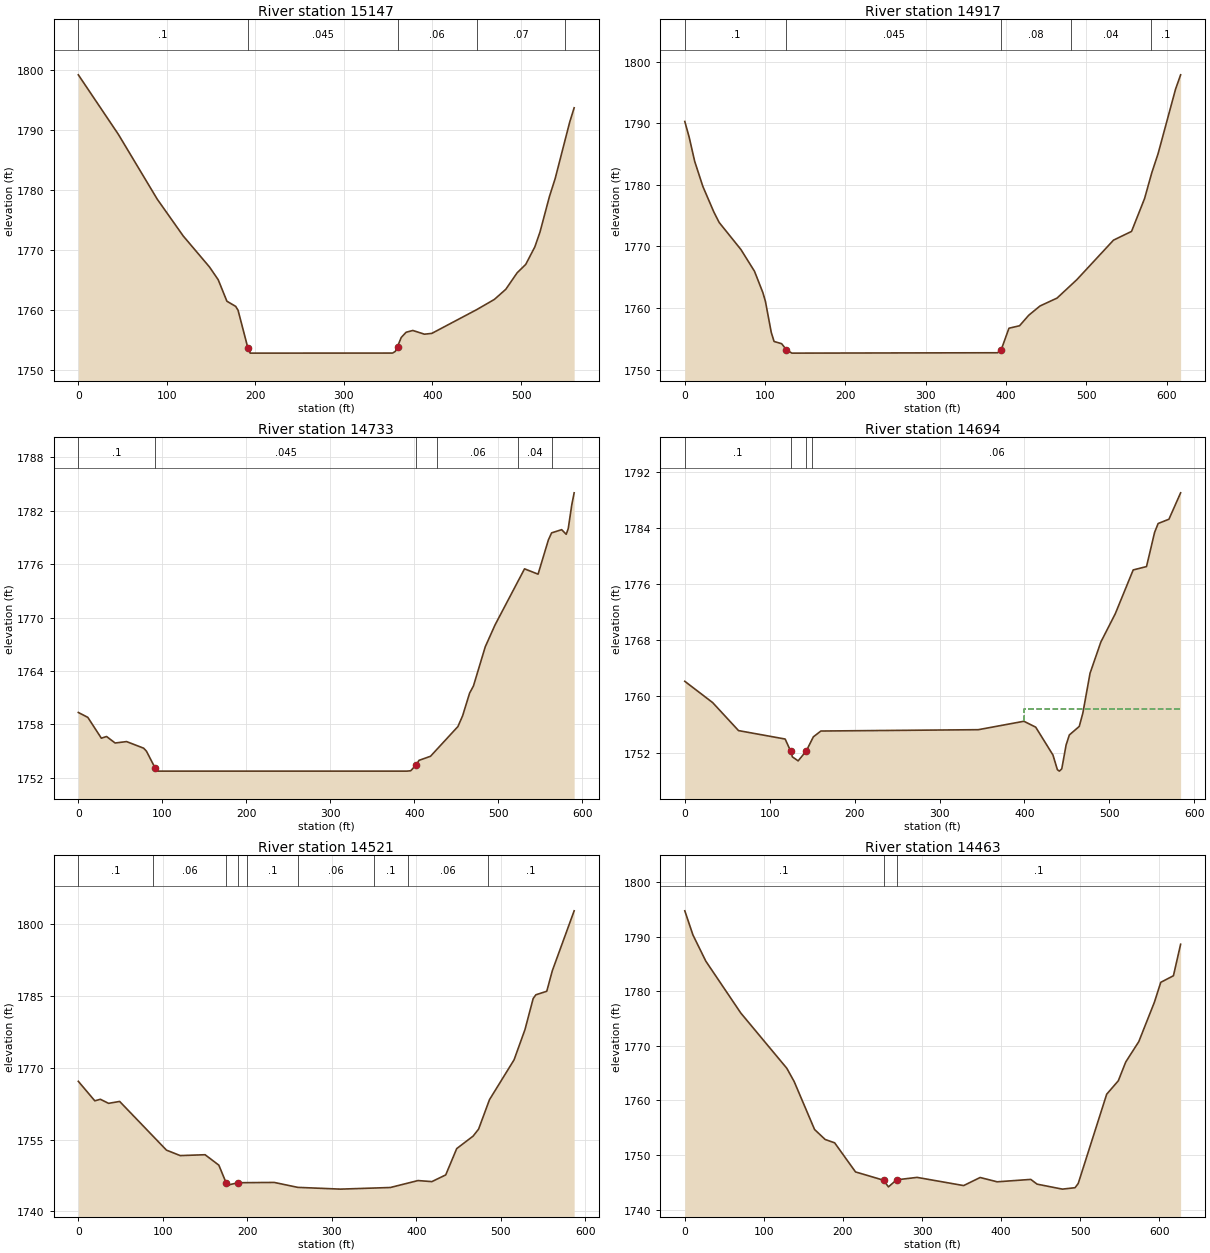
Type RM Length L Ch R = 1 ,15147   ,267.7,229.4,151.8
XS GIS Cut Line= 2
2041699.40697199213798.5818402922041688.12224981 214358.47767365
#Sta/Elev= 30
       0 1799.18    45.3 1789.23    89.1 1778.44   118.6 1772.27   148.1 1767.13
     158 1764.99   167.8 1761.41   177.7 1760.55   180.4 1759.91   191.5 1753.61
   194.1 1752.75   354.9 1752.76   358.1 1753.05   360.5 1753.84   364.7 1755.36
   370.2 1756.23   377.8 1756.53   390.9 1755.91   399.2 1756.04     450 1760.01
   469.9 1761.71   482.8  1763.4   495.6 1766.15   505.3 1767.55   515.6 1770.47
   521.4 1772.94   532.1 1778.88   538.6 1781.89     555  1791.3560.0095 1793.68
#Mann= 5 ,-1 , 0
       0      .1       0   191.5    .045       0   360.5     .06       0
     450     .07       0     550      .1       0
Bank Sta=191.5,360.5
XS Rating Curve= 0 ,0
Exp/Cntr(USF)=0,0
Exp/Cntr=0.3,0.1

Type RM Length L Ch R = 1 ,14917   ,118.7,184.5,106.8
XS GIS Cut Line= 4
2041405.09164522213796.9486581812041427.64078613213885.641945761
2041565.94218371214238.9118200232041618.55684583214375.709941546
#Sta/Elev= 30
       0 1790.28     5.5 1787.71    12.3 1783.82    22.5 1779.74    36.2 1775.59
    42.8  1773.9    69.9 1769.51    86.8 1765.98    97.2 1762.53   100.4 1761.11
   107.7 1756.05   111.2 1754.59   120.6 1754.23   126.5 1753.26   133.3  1752.7
   389.6 1752.76   394.1 1753.26   403.7 1756.74   416.9 1757.14   428.3 1758.84
   442.4 1760.35   463.6 1761.63   488.2 1764.61   533.9 1771.03   556.4 1772.45
   572.6 1777.78   581.7 1782.01   589.4 1785.04   611.2 1795.53   617.5 1797.85
#Mann= 5 ,-1 , 0
       0      .1       0   126.5    .045       0   394.1     .08       0
  480.89     .04       0  580.89      .1       0
Bank Sta=126.5,394.1
XS Rating Curve= 0 ,0
Exp/Cntr=0.3,0.1

Type RM Length L Ch R = 1 ,14733   ,53.8,39,69.6
XS GIS Cut Line= 4
2041339.60849079213900.9920727012041290.05054215214091.170700416
2041513.68078521214286.9245973832041569.43347737214365.597840786
#Sta/Elev= 30
       0 1759.34    11.3 1758.79    27.4 1756.45    33.6 1756.64    43.8 1755.91
    57.4 1756.07    77.7 1755.33    81.1 1754.99    91.3 1753.12    94.7 1752.75
   390.6 1752.75   395.6 1752.79     402 1753.44   405.5 1753.96   419.2 1754.42
   451.8 1757.76   457.4 1758.97   465.7 1761.51   470.3 1762.32   484.3 1766.71
     496 1769.18   531.1 1775.48   547.2 1774.88   559.5 1778.73   563.3 1779.52
   575.3 1779.88   580.7 1779.36   583.1 1779.99   587.4 1782.71590.1587 1784.02
#Mann= 6 ,-1 , 0
       0      .1       0    91.3    .045       0     402     .08       0
  426.53     .06       0  523.73     .04       0  563.73      .1       0
Bank Sta=91.3,402
XS Rating Curve= 0 ,0
Exp/Cntr(USF)=0,0
Exp/Cntr=0.3,0.1

Type RM Length L Ch R = 1 ,14694   ,207.9,172.5,350.8
XS GIS Cut Line= 6
2041292.52843958213904.7089188252041258.45734996214065.152777404
 2041262.7856124214105.8156127182041372.18970117214206.519461423
 2041414.2079998214240.8980693672041525.45079803214377.367853582
#Sta/Elev= 30
       0 1762.16    32.8 1759.13    63.3 1755.14   118.2 1753.94  124.71  1752.2
   126.7  1751.4   133.5 1750.83   143.1 1752.25   151.4 1754.25   160.3 1755.08
   345.7 1755.27   399.4 1756.47   413.3 1755.63   433.6 1751.67   438.8 1749.58
   441.2 1749.37     444  1749.7   449.1  1753.1   452.9 1754.52   464.6 1755.74
   468.8 1757.63   477.3 1763.31     490 1767.75     507 1771.78   528.1 1778.02
   543.8  1778.5   553.3 1783.36   557.5 1784.63   570.2 1785.24583.9684    1789
#Mann= 4 ,-1 , 0
       0      .1       0  124.71    .045       0   143.1      .1       0
     150     .06       0
#XS Ineff= 2 , 0
                           399.7         1758.28
Permanent Ineff=
       F       F
Bank Sta=124.71,143.1
XS Rating Curve= 0 ,0
Exp/Cntr(USF)=0,0
Exp/Cntr=0.3,0.1

Type RM Length L Ch R = 1 ,14521   ,53.7,58.2,63.6
XS GIS Cut Line= 5
     2041131.622      213962.761     2041157.562      214026.054
     2041165.147       214117.07     2041379.414      214304.791
     2041402.168      214445.107
#Sta/Elev= 30
       0 1767.19    19.5 1763.12    26.1 1763.44    35.8 1762.59    48.9 1762.99
   104.3 1752.81   120.6 1751.67     150 1751.85   166.3 1749.67  174.84 1746.01
   179.4 1745.61   189.2    1746   231.8 1746.06  259.731745.028   310.4 1744.66
   369.3    1745     402 1746.45   418.4 1746.23   434.8 1747.63   447.8 1753.13
   467.2 1755.74   473.7  1757.2   486.6 1763.36   515.7 1771.69   528.6 1778.01
   538.3  1784.5   541.5 1785.28   554.4 1786.02   560.9 1790.28   586.8 1802.83
#Mann= 9 ,-1 , 0
       0      .1       0    88.4     .06       0  174.84    .045       0
   189.2     .06       0  199.73      .1       0  259.73     .06       0
  349.73      .1       0  389.73     .06       0   484.6      .1       0
Bank Sta=174.84,189.2
XS Rating Curve= 0 ,0
Exp/Cntr=0.3,0.1

Type RM Length L Ch R = 1 ,14463   ,396.6,401.7,403.6
XS GIS Cut Line= 4
2040975.03984473213957.8319248282041071.38749021214069.997840456
2041289.96722322214383.4871943912041346.05018104214462.578545155
#Sta/Elev= 30
       0 1794.71    10.3 1790.29    26.6 1785.49    70.8    1776     129 1765.88
   138.3 1763.45   164.1 1754.67   177.5 1752.84   189.5 1752.23   215.9  1746.9
   251.4 1745.38   257.5 1744.16   267.8 1745.45   293.7  1745.9   352.6  1744.4
   373.5 1745.88     395 1745.09   437.5 1745.53   445.5 1744.66   477.5 1743.75
   493.5 1744.01   497.5 1744.78   533.5 1761.13   548.2 1763.59   557.6 1767.03
   574.1 1770.76   593.8 1777.96   601.9 1781.62   617.9 1782.82     627 1788.59
#Mann= 3 ,-1 , 0
       0      .1       0   251.4    .045       0   267.8      .1       0
Bank Sta=251.4,267.8
XS Rating Curve= 0 ,0
Exp/Cntr=0.3,0.1

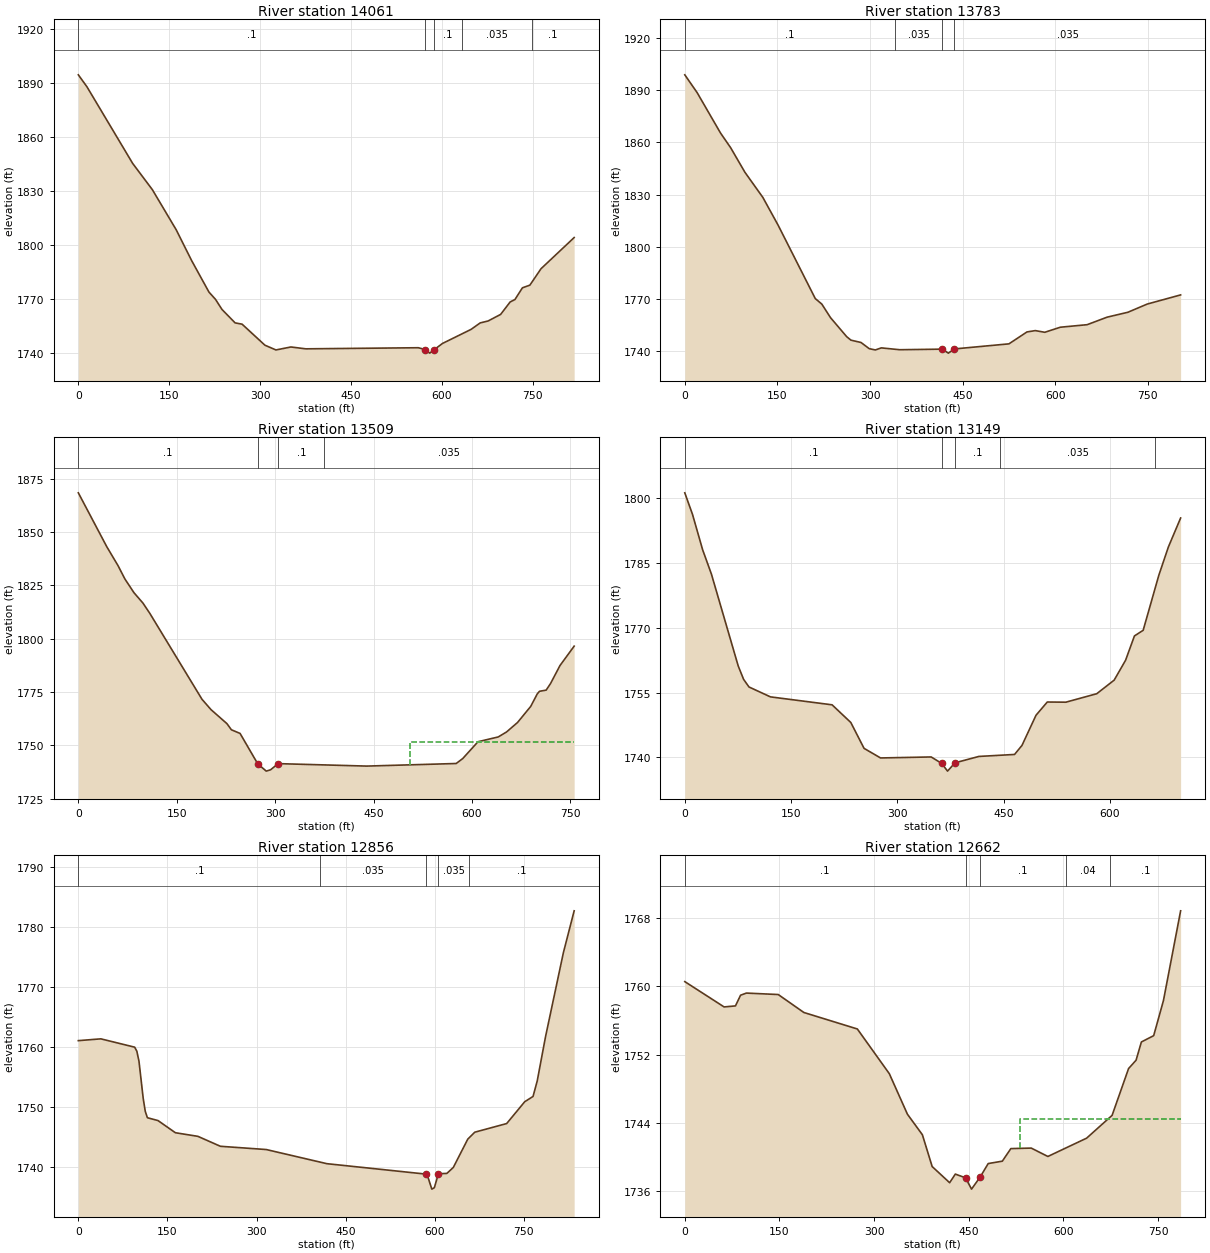
Type RM Length L Ch R = 1 ,14061   ,268,278.3,273.9
XS GIS Cut Line= 4
2040735.11115291 213960.006770332040850.96337418214217.718854361
2040988.09457485214567.6398491922041077.93915461214700.042387777
#Sta/Elev= 30
       0  1894.5    14.2 1887.88    89.7 1845.36   122.1 1830.85   161.6 1808.53
   186.8  1791.6   215.6 1774.01   226.4 1769.97   237.2 1764.33   258.8 1756.91
   270.3  1756.2     308 1744.53   326.2  1741.9   350.9 1743.55   375.5 1742.52
   561.2 1743.13   572.9 1742.08   579.9 1740.14     587 1741.95     601 1745.49
   648.2  1753.3   663.4 1756.91   676.3 1757.96     697 1761.61   712.8 1768.53
   720.7 1769.88     733 1776.37   745.3 1777.84   763.7 1786.95   818.4 1804.24
#Mann= 5 ,-1 , 0
       0      .1       0   572.9    .045       0     587      .1       0
  632.55    .035       0  748.39      .1       0
Bank Sta=572.9,587
XS Rating Curve= 0 ,0
Exp/Cntr(USF)=0,0
Exp/Cntr=0.3,0.1

Type RM Length L Ch R = 1 ,13783   ,276.5,274,265.3
XS GIS Cut Line= 4
2040665.58281292214015.7747168522040725.61570801214279.640232507
2040742.36907409214536.5251789652040856.85040892214786.429556226
#Sta/Elev= 30
       0 1898.94      20 1888.68    57.8 1865.46    74.3 1856.94    97.4 1842.81
   126.4 1828.36   151.2 1812.32   211.3 1770.11   221.9 1766.93     236  1759.1
   262.2 1748.16     269 1746.18   285.4 1744.82   298.6 1741.28   308.5 1740.53
   318.3 1741.72   347.9 1740.66   416.8 1740.99   426.8  1738.7   436.7 1741.12
   524.9 1744.04   554.1  1750.9   567.6 1751.67   582.9  1750.7   608.2 1753.62
   651.5 1755.07   683.9 1759.41   717.5 1762.23   748.9 1766.96   802.9 1772.22
#Mann= 4 ,-1 , 0
       0      .1       0  340.61    .035       0   416.8    .045       0
   436.7    .035       0
Bank Sta=416.8,436.7
XS Rating Curve= 0 ,0
Exp/Cntr(USF)=0,0
Exp/Cntr=0.3,0.1

Type RM Length L Ch R = 1 ,13509   ,369,359.7,338.7
XS GIS Cut Line= 4
 2040403.1134111214082.7881811452040474.31521691 214296.39359858
2040541.32868121214692.8899289832040567.85484416214818.540174533
#Sta/Elev= 30
       0 1868.34    43.3 1843.13    60.6 1834.19    70.9 1828.03    84.8 1821.56
    98.6 1816.65     109 1811.86   188.5 1771.62   202.3 1766.76   226.5 1760.22
   233.3 1757.35   246.5 1755.64   273.41741.424   286.4 1737.98   293.1 1738.62
   304.5 1741.49   439.5 1740.34   575.9 1741.55   585.9 1743.87   609.1 1751.74
     640 1753.99   652.6 1756.31   669.4 1760.76   689.5  1768.3   699.5 1774.17
   702.9 1775.38     713 1775.92   719.7    1779   734.1 1787.44   755.7 1796.52
#Mann= 4 ,-1 , 0
       0      .1       0   273.4    .045       0   304.5      .1       0
  375.16    .035       0
#XS Ineff= 2 , 0
                          505.44         1751.79
Permanent Ineff=
       F       F
Bank Sta=273.4,304.5
XS Rating Curve= 0 ,0
Exp/Cntr(USF)=0,0
Exp/Cntr=0.3,0.1

Type RM Length L Ch R = 1 ,13149   ,284.9,293.6,281.6
XS GIS Cut Line= 4
2040067.16789302214271.7014065492040184.50738547214475.691601118
2040365.02968155214701.3444712172040469.73261327214842.151862158
#Sta/Elev= 30
       0 1801.26    10.8 1796.31    25.2 1788.07    37.6 1782.43    75.4 1761.17
      83 1758.08    90.6 1756.31   120.9 1754.02   207.9 1752.18   234.3 1748.09
     253  1742.1   276.3 1739.88   347.7 1740.11   362.7 1738.61   370.8 1736.83
   381.3 1738.75     415 1740.23   465.4 1740.69   475.9 1742.79   495.7 1749.77
   511.6 1752.83   537.8 1752.79   581.4 1754.75     606  1757.9   622.1  1762.5
   634.6 1768.13   646.9 1769.43   669.1 1782.22   682.5 1788.72699.7766 1795.43
#Mann= 5 ,-1 , 0
       0      .1       0   362.7    .045       0   381.3      .1       0
  445.33    .035       0  664.31      .1       0
Bank Sta=362.7,381.3
XS Rating Curve= 0 ,0
Exp/Cntr(USF)=0,0
Exp/Cntr=0.3,0.1

Type RM Length L Ch R = 1 ,12856   ,188.3,194,192.8
XS GIS Cut Line= 5
2039712.56926913214440.3517034872039860.31757357214502.867913075
2040054.15389513214620.6386439072040239.91938543214881.093351951
2040324.18414392214976.848759321
#Sta/Elev= 30
       0 1761.11    37.9 1761.41    94.9 1760.02    98.5 1759.35   102.1 1757.68
   109.2  1751.5   112.7 1749.32   116.3 1748.26   134.1 1747.79   163.4 1745.76
   201.2 1745.16   239.2  1743.5   316.3 1742.96   418.5  1740.6   584.6 1738.87
   587.4 1738.71   595.1 1736.36   599.3 1736.59   606.2 1738.92   620.4 1738.98
   631.3 1739.98   655.6 1744.69   667.4 1745.85   721.1 1747.29   751.5 1750.93
   765.5 1751.81   772.5 1754.38   786.6 1761.81   816.6 1775.79   834.7 1782.75
#Mann= 5 ,-1 , 0
       0      .1       0  407.24    .035       0   584.6    .045       0
   606.2    .035       0  657.24      .1       0
Bank Sta=584.6,606.2
XS Rating Curve= 0 ,0
Exp/Cntr(USF)=0,0
Exp/Cntr=0.3,0.1

Type RM Length L Ch R = 1 ,12662   ,202.1,179.6,151.7
XS GIS Cut Line= 4
 2039695.7157519 214490.302888522039952.04225282214732.807862432
2040042.51042962214901.1791914692040246.06382741215031.855446841
#Sta/Elev= 30
       0 1760.54    62.3 1757.58    80.3  1757.7    88.4 1758.95    97.7  1759.2
   148.1 1759.03   188.7 1756.93   273.5    1755   324.2 1749.77   352.9 1745.03
   376.6 1742.63   392.1 1738.91   419.8 1737.02   428.8 1738.03     445 1737.59
   454.5 1736.27   468.3  1737.7   480.9 1739.26   503.3 1739.54   516.8 1741.01
   549.1 1741.07   575.5 1740.09   636.9 1742.23   677.3  1744.9   703.4 1750.37
   715.3 1751.35   723.7 1753.48   743.2 1754.22   758.7 1758.33   785.9 1768.82
#Mann= 5 ,-1 , 0
       0      .1       0     445    .045       0   468.3      .1       0
     604     .04       0     674      .1       0
#XS Ineff= 2 , 0
                          531.81          1744.5
Permanent Ineff=
       F       F
Bank Sta=445,468.3
XS Rating Curve= 0 ,0
Exp/Cntr(USF)=0,0
Exp/Cntr=0.3,0.1

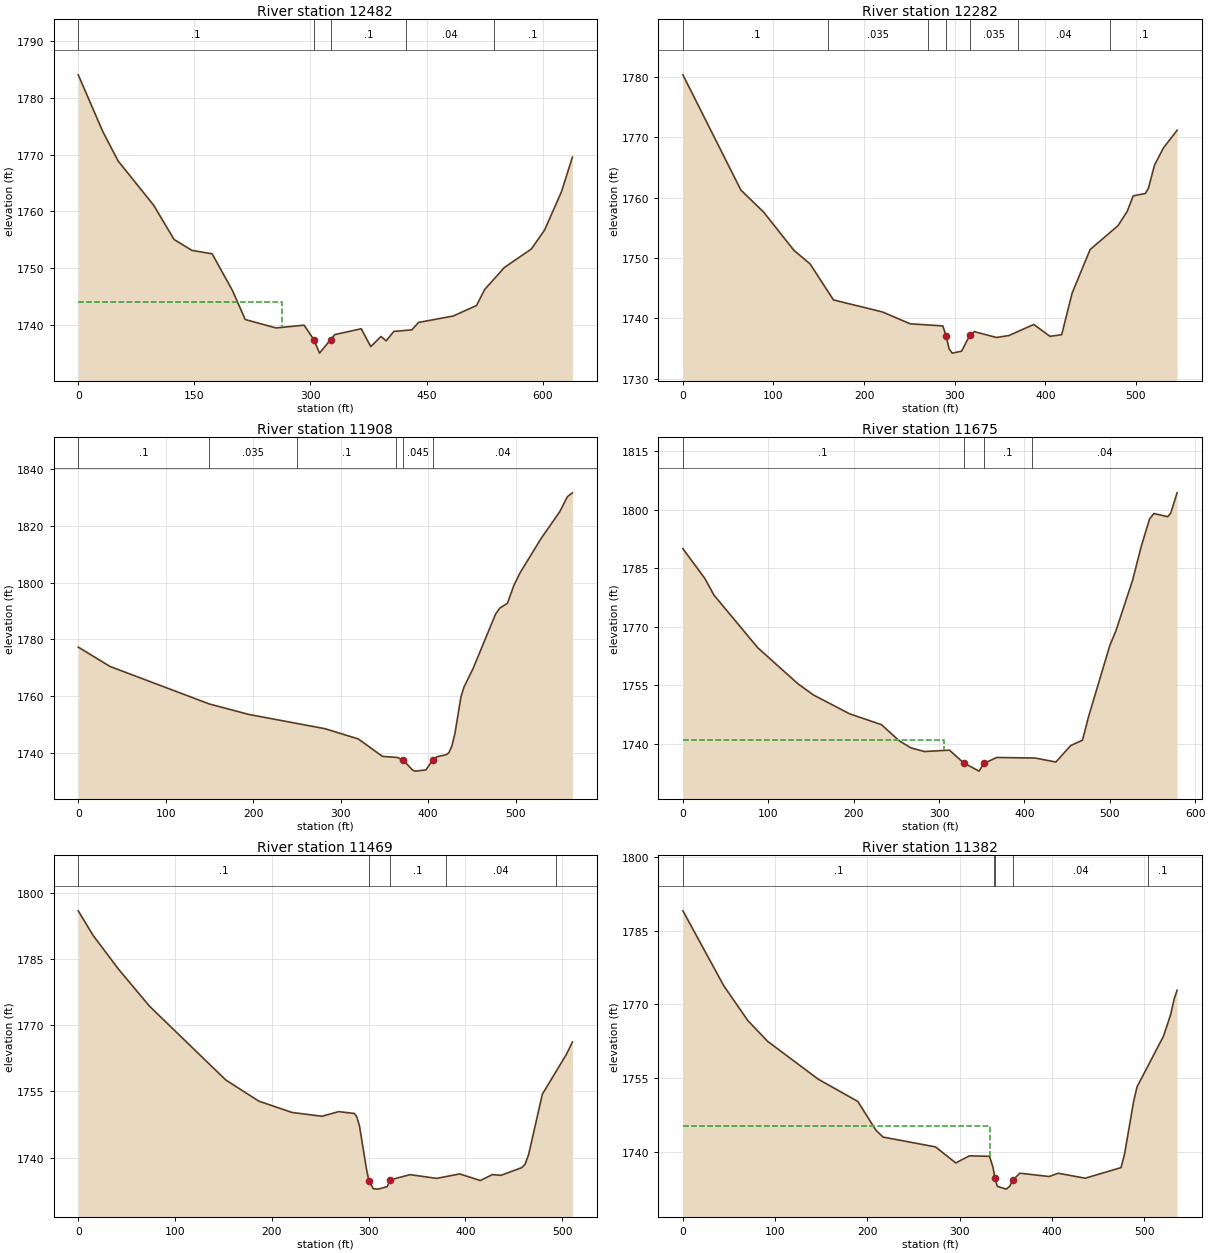
Type RM Length L Ch R = 1 ,12482   ,201.5,199.8,200.1
XS GIS Cut Line= 4
2039630.37762422214966.517319155 2039854.0350613214975.312836343
2040085.23151311214943.9002749562040238.52481268215040.650964029
#Sta/Elev= 30
       0 1784.08    31.8 1774.05    51.5 1768.89    97.5 1761.06   123.8 1755.03
   146.8 1753.11     173  1752.5   199.3    1746   215.7 1740.91   255.4 1739.43
   291.8 1739.91   304.3 1737.37   311.7 1734.98     326 1737.37   331.5 1738.25
   365.6 1739.28   377.9 1736.13   391.1 1737.92   397.8 1737.15   407.7 1738.81
   430.9 1739.09   439.7  1740.4   484.5 1741.53   514.5 1743.38     525  1746.2
   550.5 1750.09   585.4 1753.36   602.5 1756.71   624.2 1763.44   638.4 1769.56
#Mann= 5 ,-1 , 0
       0      .1       0   304.3    .045       0     326      .1       0
  423.83     .04       0  537.15      .1       0
#XS Ineff= 2 , 0
          262.75 1744.04
Permanent Ineff=
       F       F
Bank Sta=304.3,326
XS Rating Curve= 0 ,0
Exp/Cntr(USF)=0,0
Exp/Cntr=0.3,0.1

Type RM Length L Ch R = 1 ,12282   ,362.9,374.1,347.4
XS GIS Cut Line= 4
  2039707.024274215227.8698298992039838.95703183 215180.12273659
2040122.92658677 215079.602540152040224.70328567215058.241998406
#Sta/Elev= 30
       0 1780.33      64 1761.25    89.3 1757.57   122.6 1751.26   140.3 1749.04
   166.2 1743.06   220.2 1741.07     251  1739.1   286.9 1738.76   290.4 1737.16
   293.9 1734.95   297.3 1734.25   307.6 1734.57   316.9 1737.25   321.7 1737.81
   346.1 1736.84     360 1737.17   387.3    1739   405.2 1737.03   418.1  1737.3
   429.6 1744.17   449.5  1751.4   480.3 1755.36   490.4  1757.7   497.1 1760.29
   510.5 1760.69   513.9 1761.57   520.6 1765.39   530.6 1768.27   545.5 1771.14
#Mann= 7 ,-1 , 0
       0      .1       0  160.31    .035       0  270.31      .1       0
   290.4    .045       0   316.9    .035       0  370.31     .04       0
  471.54      .1       0
Bank Sta=290.4,316.9
XS Rating Curve= 0 ,0
Exp/Cntr(USF)=0,0
Exp/Cntr=0.3,0.1

Type RM Length L Ch R = 1 ,11908   ,230.6,233.8,232.2
XS GIS Cut Line= 4
2039816.33998763215446.5012571562040111.61806467 215342.21155335
2040249.83333478215296.9774649522040346.58402385215252.999879009
#Sta/Elev= 30
       0 1777.28    36.4 1770.46   149.7 1757.28   194.9 1753.58   281.9 1748.57
   320.1 1744.96   347.7 1738.83     365 1738.42  371.791737.398   382.3 1733.95
   385.7 1733.62   397.4 1734.05  405.021737.396   409.9 1738.66   420.8 1739.43
   423.7  1740.1   427.1 1742.44   430.6 1746.89   437.5 1759.79   440.9 1763.21
   451.3 1769.71   477.1 1788.95     482 1791.04   490.6 1792.71   497.8 1798.88
     505 1803.42   529.1 1815.53   550.4 1824.95   559.1 1830.23   564.9  1831.6
#Mann= 6 ,-1 , 0
       0      .1       0     150    .035       0     250      .1       0
  363.15     .04       0  371.79    .045       0  405.02     .04       0
Bank Sta=371.79,405.02
XS Rating Curve= 0 ,0
Exp/Cntr(USF)=0,0
Exp/Cntr=0.3,0.1

Type RM Length L Ch R = 1 ,11675   ,204.9,205.5,201.1
XS GIS Cut Line= 4
2039896.75614478215646.2851475812040086.48801556215585.973029717
2040346.58402385215498.0178578322040443.33471293  215456.5532768
#Sta/Elev= 30
       0 1789.99    25.8 1782.33    36.2 1778.14    87.8 1764.56   134.7 1755.35
   153.2 1752.43   195.4 1747.62   232.6 1744.85   253.4 1740.71   267.2 1738.88
   282.9 1737.96   312.3 1738.31   328.8 1735.05   346.9 1732.93   352.7 1734.92
   367.7 1736.43   412.7 1736.29   436.9 1735.26   454.3 1739.49   468.1 1740.87
   475.1 1746.82   500.1 1765.15   507.2 1768.89   526.8  1781.9   536.7 1790.41
   546.7 1797.64   551.7 1799.01   567.9  1798.2   571.5 1799.13   578.9 1804.32
#Mann= 4 ,-1 , 0
       0      .1       0   328.8    .045       0   352.7      .1       0
  409.09     .04       0
#XS Ineff= 2 , 0
          305.71 1741.03
Permanent Ineff=
       F       F
Bank Sta=328.8,352.7
XS Rating Curve= 0 ,0
Exp/Cntr(USF)=0,0
Exp/Cntr=0.3,0.1

Type RM Length L Ch R = 1 ,11469   ,101.9,87,73
XS GIS Cut Line= 4
2039988.48082403215810.8869692522040237.26831022215736.753324377
2040351.61003367215687.7497286132040468.46476204215638.746132848
#Sta/Elev= 30
       0 1795.95    15.2 1790.43    41.6 1782.72    73.8 1774.29   152.5 1757.58
   186.6 1752.79   220.9 1750.22   251.8 1749.36   269.3 1750.41   285.4 1749.99
   287.9 1749.21   290.7 1747.08   297.9 1737.34   300.4  1734.7     305 1732.91
   310.2 1732.83   319.3  1733.4   322.31734.925   342.9 1736.11   370.4 1735.27
   394.2 1736.28   415.5 1734.78     428 1736.13   436.9 1735.96   458.2 1737.69
   461.8 1738.47   465.4 1740.64   479.6 1754.35   504.5  1763.4   510.7  1766.2
#Mann= 5 ,-1 , 0
       0      .1       0   300.4    .045       0   322.3      .1       0
   379.6     .04       0     494      .1       0
Bank Sta=300.4,322.3
XS Rating Curve= 0 ,0
Exp/Cntr(USF)=0,0
Exp/Cntr=0.3,0.1

Type RM Length L Ch R = 1 ,11382   ,112,92.2,74.9
XS GIS Cut Line= 4
2040146.80013343216047.1094308862040308.88895019215859.890565016
2040391.81811225215692.7757384352040478.51678168215640.002635304
#Sta/Elev= 30
       0    1789    44.3  1773.8    70.4 1766.73    91.7 1762.55   146.8 1754.83
   189.6 1750.33   209.2  1744.5     217  1743.1   273.8 1741.11   295.8 1737.85
   310.5 1739.29   332.4  1739.2   336.1 1736.99   338.3 1734.79   340.8 1733.11
   350.5 1732.54   354.4 1733.14   357.5 1734.34   365.2 1735.77   397.1  1735.1
   406.8 1735.76   436.2 1734.76     475 1736.91   478.8 1739.71   488.7 1750.43
   492.3 1753.29     521 1763.58   528.7 1767.93   532.6 1771.16   535.7 1772.87
#Mann= 5 ,-1 , 0
       0      .1       0  337.64     .04       0   338.3    .045       0
   357.5     .04       0   504.2      .1       0
#XS Ineff= 2 , 0
          333.04 1745.32
Permanent Ineff=
       F       F
Bank Sta=338.3,357.5
XS Rating Curve= 0 ,0
Exp/Cntr(USF)=0,0
Exp/Cntr=0.5,0.3

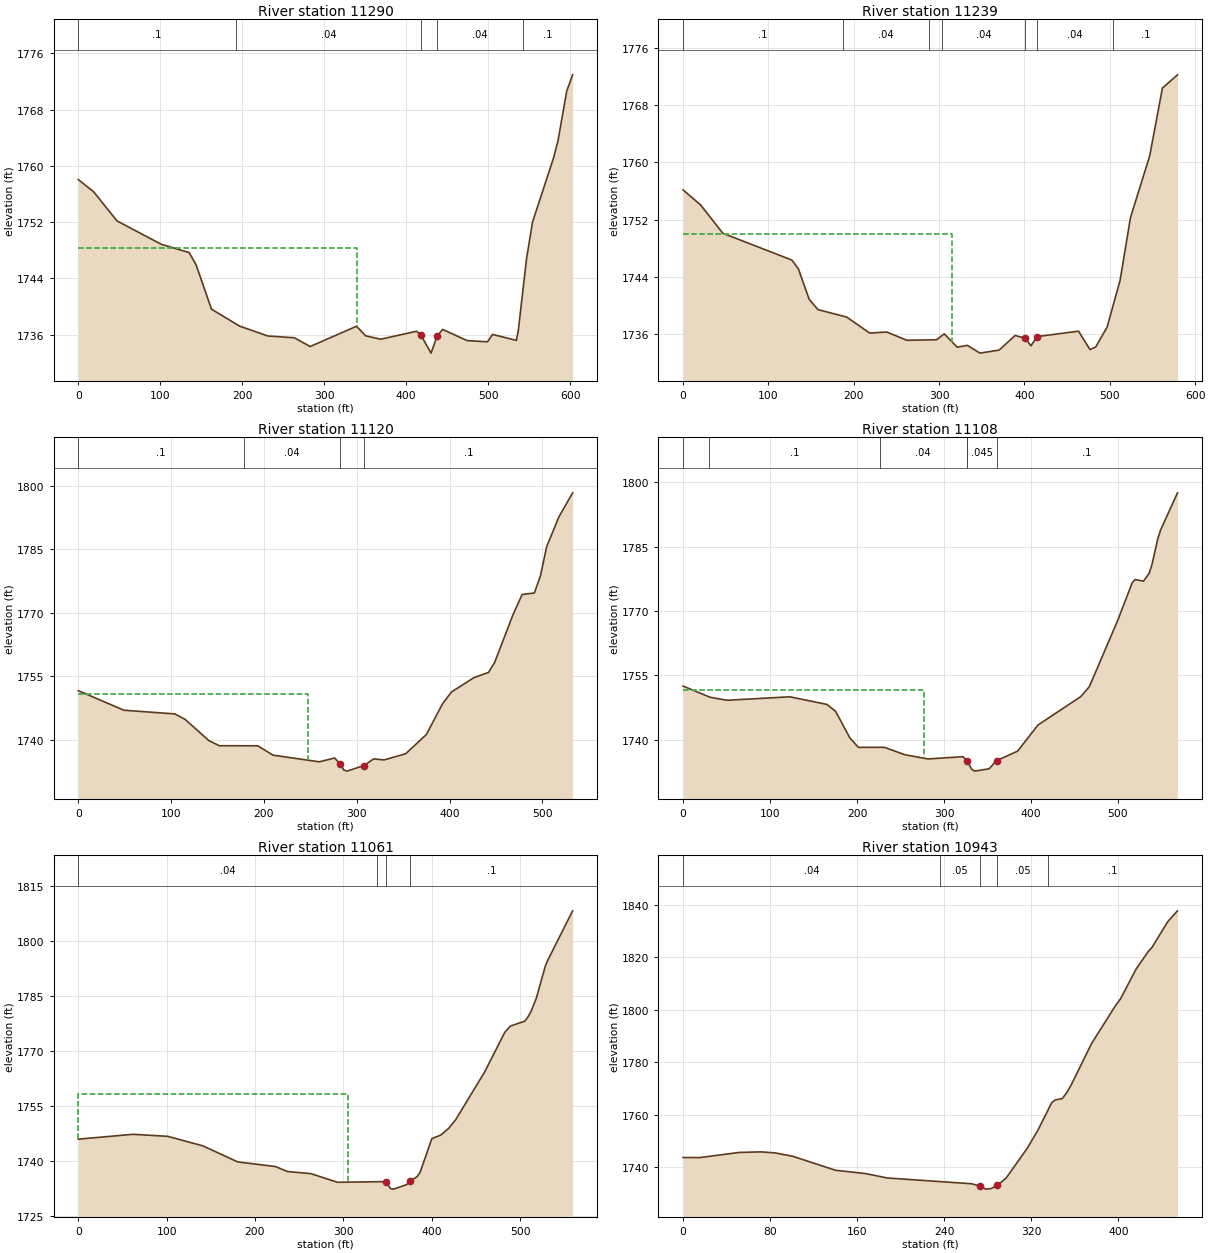
Type RM Length L Ch R = 1 ,11290   ,146.8,51.2,51.1
XS GIS Cut Line= 5
2040445.84771784216163.9641592482040550.13742164216014.440367043
2040459.66924485215825.964998718 2040415.6916589215735.496821922
 2040483.5427915215647.541650037
#Sta/Elev= 30
       0 1758.05    18.8  1756.3    47.3 1752.16   101.3 1748.84   135.3 1747.66
   143.7 1745.94   162.5 1739.62   196.8 1737.21   231.2 1735.81   263.6 1735.55
   282.9 1734.31   339.4 1737.19   350.6 1735.83   368.9 1735.35   412.6 1736.48
   417.9 1735.95   430.3 1733.37   437.7 1735.79   444.4 1736.74   474.4 1735.15
   499.1 1734.98   505.4 1736.03   534.4 1735.18   536.7 1736.56   546.8 1746.81
   554.1 1752.01   579.7 1761.11   585.1 1763.53   595.8 1770.62     603 1772.93
#Mann= 5 ,-1 , 0
       0      .1       0   192.3     .04       0   417.9    .045       0
   437.7     .04       0  541.96      .1       0
#XS Ineff= 2 , 0
          339.53 1748.35
Permanent Ineff=
       F       F
Bank Sta=417.9,437.7
XS Rating Curve= 0 ,0
Exp/Cntr(USF)=0,0
Exp/Cntr=0.5,0.3

Type RM Length L Ch R = 1 ,11239   ,21.6,118.2,109.9
XS GIS Cut Line= 6
2040472.34632081216169.0069510132040568.52530126216007.792659961
2040547.45752459215904.2857571842040466.85037907215754.063349614
2040457.69047617 215704.599873952040497.99404893215653.304417707
#Sta/Elev= 30
       0 1756.14    20.5 1754.04    46.5 1750.08   127.5 1746.32   135.1 1745.09
   147.7 1740.84     158 1739.39   191.8 1738.34   218.6 1736.11   238.7 1736.25
   262.2  1735.1     297 1735.17     306    1736   321.2 1734.13   333.1 1734.39
   347.9  1733.3   370.4 1733.73   389.1 1735.77   401.2 1735.37   407.6 1734.32
     415 1735.62   463.4 1736.37   476.8  1733.8   483.5 1734.16   496.9 1736.94
   512.1 1743.49   524.3 1752.28   546.8  1760.9   561.7 1770.39   579.4 1772.25
#Mann= 7 ,-1 , 0
       0      .1       0  187.72     .04       0  287.72      .1       0
  303.35     .04       0   401.2    .045       0     415     .04       0
  503.84      .1       0
#XS Ineff= 2 , 0
          314.95 1749.95
Permanent Ineff=
       F       F
Bank Sta=401.2,415
XS Rating Curve= 0 ,0
Exp/Cntr(USF)=0,0
Exp/Cntr=0.5,0.3

Type RM Length L Ch R = 1 ,11120   ,13.1,12.2,18.1
XS GIS Cut Line= 5
 2040506.1598357 216168.990169072040581.54998303216018.209874409
2040565.21545111215915.1766730582040548.88091919215815.912979074
2040563.95894865215657.593669681
#Sta/Elev= 30
       0 1751.59    49.2 1746.96     104 1746.09     115 1744.81   140.7 1739.79
   151.9 1738.57   193.3 1738.56   209.8 1736.34   259.6 1734.77   276.2 1735.67
   282.2 1734.22   286.2 1732.81   289.5 1732.57   307.8  1733.9   318.2 1735.46
   329.4 1735.22   352.7 1736.68     375 1741.24   392.4  1748.5     402 1751.27
   426.1 1754.65   441.9  1755.9   448.5 1758.26   468.2  1769.5   478.1 1774.31
   491.3 1774.67   497.9 1778.78   504.5 1785.59   517.7 1792.65   532.5 1798.34
#Mann= 4 ,-1 , 0
       0      .1       0  178.58     .04       0   282.2    .045       0
   307.8      .1       0
#XS Ineff= 2 , 0
          247.18 1750.85
Permanent Ineff=
       F       F
Bank Sta=282.2,307.8
XS Rating Curve= 0 ,0
Exp/Cntr(USF)=0,0
Exp/Cntr=0.5,0.3

Type RM Length L Ch R = 1 ,11108   ,46.3,47.3,46.7
XS GIS Cut Line= 4
2040599.14101741216238.0978041222040597.88451495216021.979381776
2040567.72845602215873.7120920272040572.75446584215672.671699147
#Sta/Elev= 30
       0  1752.5    30.9  1749.9    50.6 1749.19   122.8    1750   165.5 1748.21
   175.3 1746.61   191.7 1740.42   201.5  1738.2   231.4 1738.22   254.8 1736.49
   281.6  1735.5   321.8 1736.03   326.7    1735   331.8 1733.11   335.2 1732.66
   351.8  1733.2   360.5 1735.11   384.6 1737.31     408 1743.41   457.2 1750.04
   467.1 1752.35   499.9  1767.9   516.3 1776.56   519.6 1777.34   529.4 1776.98
     536 1778.84   539.3 1780.98   545.8 1786.87   549.1 1788.93   568.5 1797.58
#Mann= 6 ,-1 , 0
       0     .04       0      30      .1       0  226.12     .04       0
  326.12      .1       0   326.7    .045       0   360.5      .1       0
#XS Ineff= 2 , 0
          277.43  1751.6
Permanent Ineff=
       F       F
Bank Sta=326.7,360.5
XS Rating Curve= 0 ,0
Exp/Cntr(USF)=0,0
Exp/Cntr=0.5,0.3

Type RM Length L Ch R = 1 ,11061   ,105.5,117.9,133.6
XS GIS Cut Line= 4
2040659.45313527216249.4063262222040646.88811072216042.083421064
2040606.68003214215825.964998718 2040607.9365346 215694.03224089
#Sta/Elev= 30
       0 1745.85      62 1747.17   101.2 1746.62   140.9 1744.03   180.4 1739.64
   223.3 1738.37   236.7 1737.02   263.4 1736.43   293.4 1734.08   347.9 1734.26
   353.5 1732.34   356.8 1732.21   371.5 1733.43     376 1734.43   383.5 1735.63
   386.9 1736.81   400.2 1746.01   410.2 1746.95   419.1 1748.77   426.9 1751.06
   459.8 1764.13   482.7    1775   489.2 1776.73   505.3 1778.04   508.6 1779.08
   512.2 1780.57   518.3 1784.24   528.6 1793.09   531.3 1794.65   559.5 1808.16
#Mann= 4 ,-1 , 0
       0     .04       0   337.7      .1       0   347.9    .045       0
     376      .1       0
#XS Ineff= 2 , 0
          304.91  1758.3
Permanent Ineff=
       F       F
Bank Sta=347.9,376
XS Rating Curve= 0 ,0
Exp/Cntr(USF)=0,0
Exp/Cntr=0.5,0.3

Type RM Length L Ch R = 1 ,10943   ,101.3,109.8,117
XS GIS Cut Line= 4
2040668.24865246216235.5847992112040668.24865246216079.778494729
2040724.79126296 215920.202682882040785.10338082 215805.86095943
#Sta/Elev= 30
       0 1743.78    15.3 1743.76    51.4 1745.71    71.1 1745.93    84.2 1745.56
   100.6 1744.28     140 1738.93   167.4 1737.69   187.7 1735.99   265.1  1733.8
   272.8 1732.92   278.2 1731.75   283.1 1731.97   288.7 1733.14   296.8 1735.93
   316.5 1747.44     326 1754.12   338.8 1764.67   341.9 1765.69   348.6 1766.26
   353.1 1768.81   356.8 1771.53   375.4 1787.18   397.1 1801.42     402 1804.18
   416.5 1815.65   427.2 1822.05   431.1 1823.87   445.5 1833.61   454.4  1837.7
#Mann= 5 ,-1 , 0
       0     .04       0  235.81     .05       0   272.8    .045       0
   288.7     .05       0   335.1      .1       0
Bank Sta=272.8,288.7
XS Rating Curve= 0 ,0
Exp/Cntr(USF)=0,0
Exp/Cntr=0.3,0.1

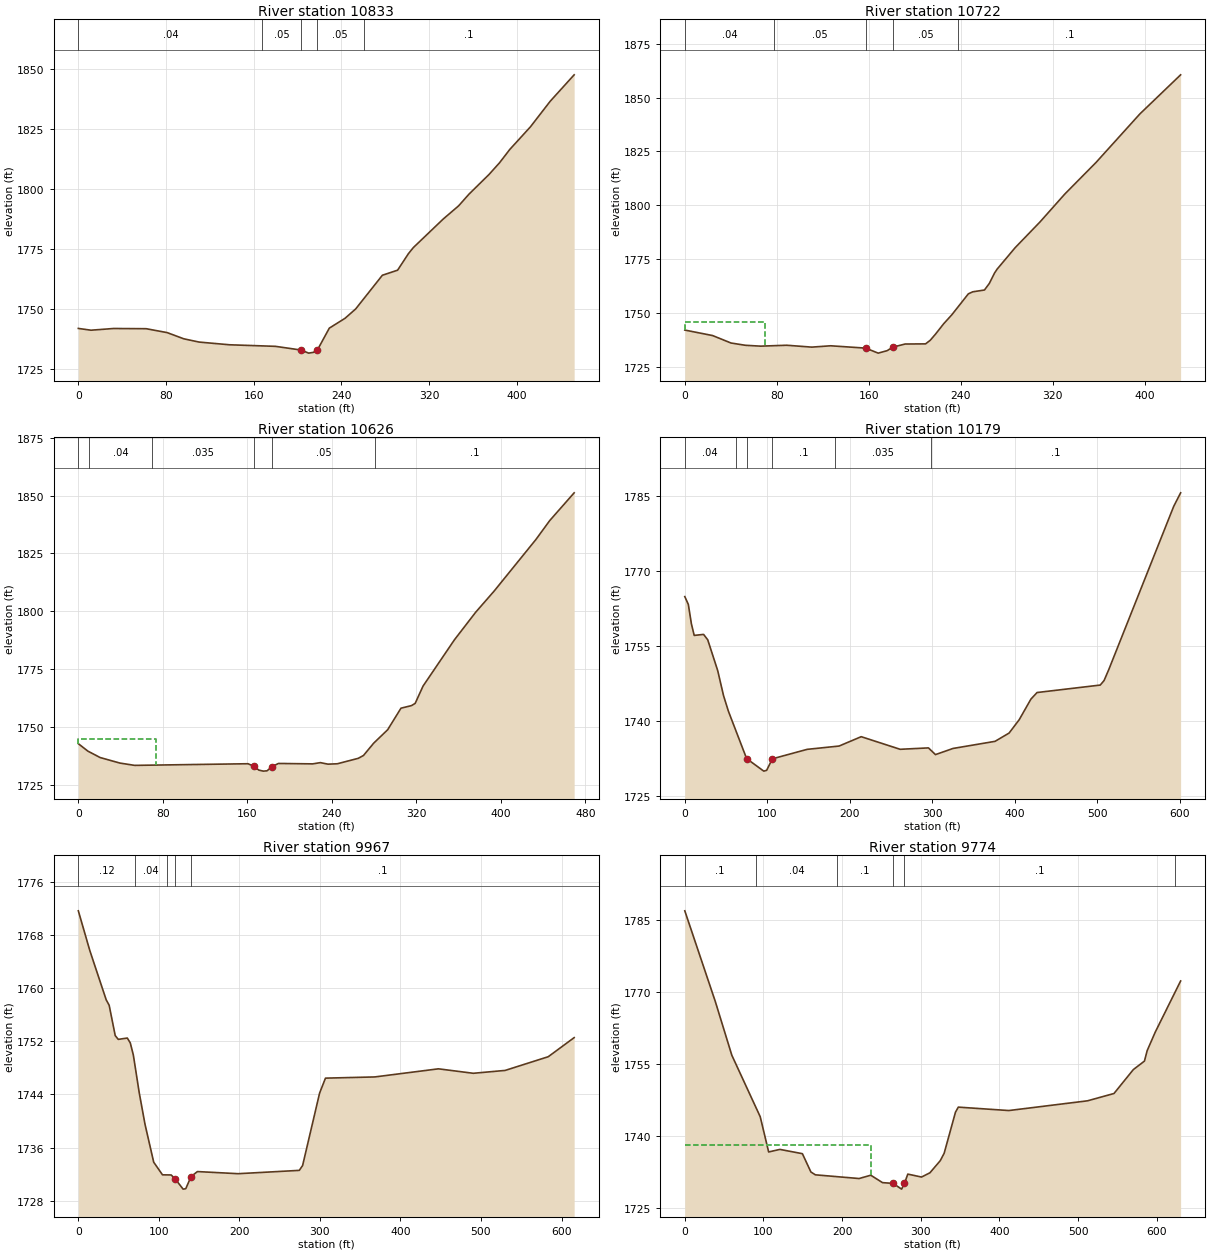
Type RM Length L Ch R = 1 ,10833   ,108.8,111.4,111.9
XS GIS Cut Line= 4
2040677.04416965216225.5327795672040690.86569666216138.834110138
2040808.97692748216013.1838645872040943.42269021215876.225096938
#Sta/Elev= 30
       0 1741.89    11.6 1741.15    31.9 1741.86    61.8 1741.78      81 1740.15
    96.2 1737.56   110.2  1736.2   137.9 1735.07   179.8 1734.42     203 1732.88
   210.1 1731.59   214.6 1731.93   217.31732.903   219.2 1733.87   228.9 1742.01
   243.3 1746.14   252.9    1750   277.3 1764.08   291.2  1766.2     301 1773.05
   305.6 1775.65   332.9 1787.58   346.9 1793.06   356.1 1797.82   374.6 1806.14
   384.2 1811.03   393.5 1816.56   412.3 1825.98   430.4 1836.69   452.2 1847.69
#Mann= 5 ,-1 , 0
       0     .04       0  167.79     .05       0     203    .045       0
   217.3     .05       0  260.24      .1       0
Bank Sta=203,217.3
XS Rating Curve= 0 ,0
Exp/Cntr(USF)=0,0
Exp/Cntr=0.3,0.1

Type RM Length L Ch R = 1 ,10722   ,93.2,95.8,104.2
XS GIS Cut Line= 4
2040684.58318438216248.1498237662040708.45673104216234.328296756
 2040881.8540699216102.3955389282041012.53032527  215970.4627811
#Sta/Elev= 30
       0 1741.96    24.2  1739.4    40.2 1735.94    52.7 1734.88    65.9 1734.48
    88.7  1734.9   110.4 1734.03   126.9 1734.65   157.2 1733.57   168.2 1731.24
     176 1732.39   180.8    1734   191.6 1735.47   209.4 1735.54   213.5 1737.24
   218.1 1740.11   225.1 1744.86   232.2 1749.04   246.6 1758.79   250.4 1759.73
   260.6 1760.57   264.8 1763.59   269.4 1768.48   271.7 1770.32   287.3 1780.24
   308.8 1792.13   330.5 1805.17   357.6 1819.82   395.8 1842.41   431.2 1860.56
#Mann= 5 ,-1 , 0
       0     .04       0   77.59     .05       0   157.2    .045       0
   180.8     .05       0  237.59      .1       0
#XS Ineff= 2 , 0
           69.48 1745.78
Permanent Ineff=
       F       F
Bank Sta=157.2,180.8
XS Rating Curve= 0 ,0
Exp/Cntr(USF)=0,0
Exp/Cntr=0.3,0.1

Type RM Length L Ch R = 1 ,10626   ,448.8,447,427
XS GIS Cut Line= 4
2040682.07017947216312.2314489972040785.10338082216270.766867965
2040939.65318285216200.402730457 2041076.6119505 216070.98297754
#Sta/Elev= 30
       0 1742.88       9 1739.67    20.6  1736.9    39.4  1734.5    53.4 1733.51
   160.6 1734.22   165.9 1733.18   170.8 1731.48     175 1731.03   178.6 1731.16
   183.2 1732.94   189.4 1734.34   221.9 1734.16   229.1  1734.7   236.3 1734.04
   245.1  1734.2     265 1736.56   269.9 1737.79   279.5 1743.07   292.8  1748.9
   305.4  1758.2   315.3 1759.31   318.8 1760.26   326.3 1767.76     356 1787.73
   376.1 1799.62   393.6 1808.77   433.1 1831.01   446.2 1839.19   469.3 1851.16
#Mann= 6 ,-1 , 0
       0      .1       0      10     .04       0      70    .035       0
   165.9    .045       0   183.2     .05       0  280.88      .1       0
#XS Ineff= 2 , 0
           73.78 1744.72
Permanent Ineff=
       F       F
Bank Sta=165.9,183.2
XS Rating Curve= 0 ,0
Exp/Cntr(USF)=0,0
Exp/Cntr=0.3,0.1

Type RM Length L Ch R = 1 ,10179   ,215.3,211.5,209.1
XS GIS Cut Line= 4
2040672.01815983216528.3498713432040719.76525314216508.245832055
2040886.88007972216450.4467191022041174.61914203216214.224257468
#Sta/Elev= 30
       0 1764.83     4.3 1763.26       8 1759.39    11.4 1757.08    22.8 1757.28
    27.8  1756.2    39.9 1750.04      47 1745.02    52.9 1741.92    74.9 1732.48
    95.7 1729.97    99.2 1730.13   106.1 1732.43   148.3 1734.32     187 1734.98
   213.8 1736.85     261 1734.33   295.3 1734.61   303.8 1733.27   325.1  1734.5
     376 1735.92     393 1737.57   405.2 1740.22   419.5 1744.36   426.9 1745.67
   503.5 1747.16   508.1 1748.06   513.8 1750.24   592.5 1782.85   600.9 1785.56
#Mann= 6 ,-1 , 0
       0     .04       0   61.81      .1       0    74.9    .045       0
   106.1      .1       0  181.81    .035       0  298.63      .1       0
Bank Sta=74.9,106.1
XS Rating Curve= 0 ,0
Exp/Cntr(USF)=0,0
Exp/Cntr=0.3,0.1

Type RM Length L Ch R = 1 ,9967    ,188.2,193.6,188
XS GIS Cut Line= 4
2040747.40830716216735.6727765012040808.97692748216701.747210202
2041023.83884737216602.483516218 2041305.2953974216475.576768212
#Sta/Elev= 30
       0  1771.6    14.2 1765.65    34.6 1758.22    38.3  1757.4    45.8 1752.84
    49.6 1752.27    60.8 1752.47    64.5 1751.74    68.3 1749.93    75.6 1744.26
    82.8  1739.5    93.6  1733.8   104.5  1731.9   115.3 1731.88   120.3 1731.28
   130.1 1729.75   133.4 1729.81     140 1731.64   147.9 1732.39   198.5 1732.07
   274.4 1732.57   278.5  1733.3   299.6 1744.19   306.9 1746.44   368.1 1746.62
   447.2 1747.84   490.4 1747.17     530  1747.6   583.5 1749.66   615.7 1752.53
#Mann= 5 ,-1 , 0
       0     .12       0      70     .04       0   110.3      .1       0
   120.3    .045       0     140      .1       0
Bank Sta=120.3,140
XS Rating Curve= 0 ,0
Exp/Cntr(USF)=0,0
Exp/Cntr=0.3,0.1

Type RM Length L Ch R = 1 ,9774    ,191.8,187.5,179.9
XS GIS Cut Line= 4
2040764.99934153216870.1185392392040896.93209936216813.575928742
2041115.56352662216714.3122347572041345.50347598216625.100560417
#Sta/Elev= 30
       0 1786.82    38.8 1767.98    59.8 1756.82    95.9 1744.05   106.6 1736.74
   120.9 1737.27   149.5 1736.38   160.3 1732.58     166 1731.99   221.6 1731.22
   236.4 1731.91   251.3 1730.37   264.8 1730.21   275.6 1729.02   279.2  1730.2
   283.5 1732.14   300.9 1731.53   311.6 1732.41   324.8 1734.94   329.7 1736.47
   344.1    1745   347.7 1746.05   411.9 1745.34   511.9 1747.36   545.6 1748.88
   570.2 1753.85   584.3 1755.61   587.8 1757.79   598.1 1761.65   630.3 1772.25
#Mann= 6 ,-1 , 0
       0      .1       0      90     .04       0  193.54      .1       0
   264.8    .045       0   279.2      .1       0  623.65     .06       0
#XS Ineff= 2 , 0
          236.83 1738.24
Permanent Ineff=
       F       F
Bank Sta=264.8,279.2
XS Rating Curve= 0 ,0
Exp/Cntr(USF)=0,0
Exp/Cntr=0.3,0.1