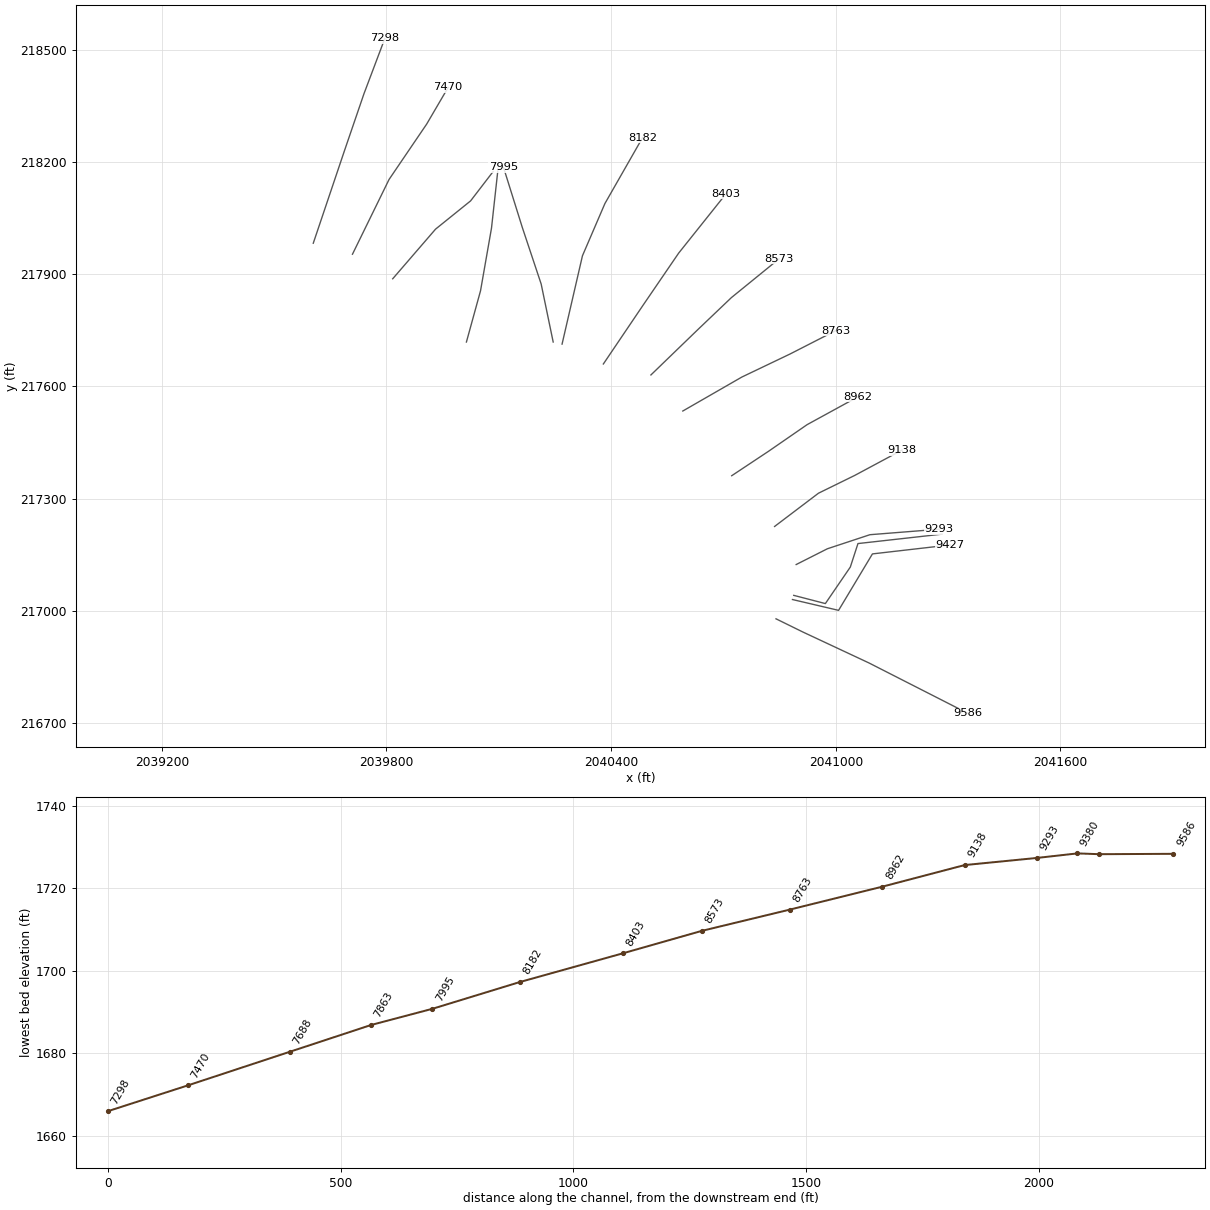
HEC-RAS study LTLSTNYCK.prj: LTLSTNYCK

--- LTLSTNYCK.g01 (geometry) --- (continued)

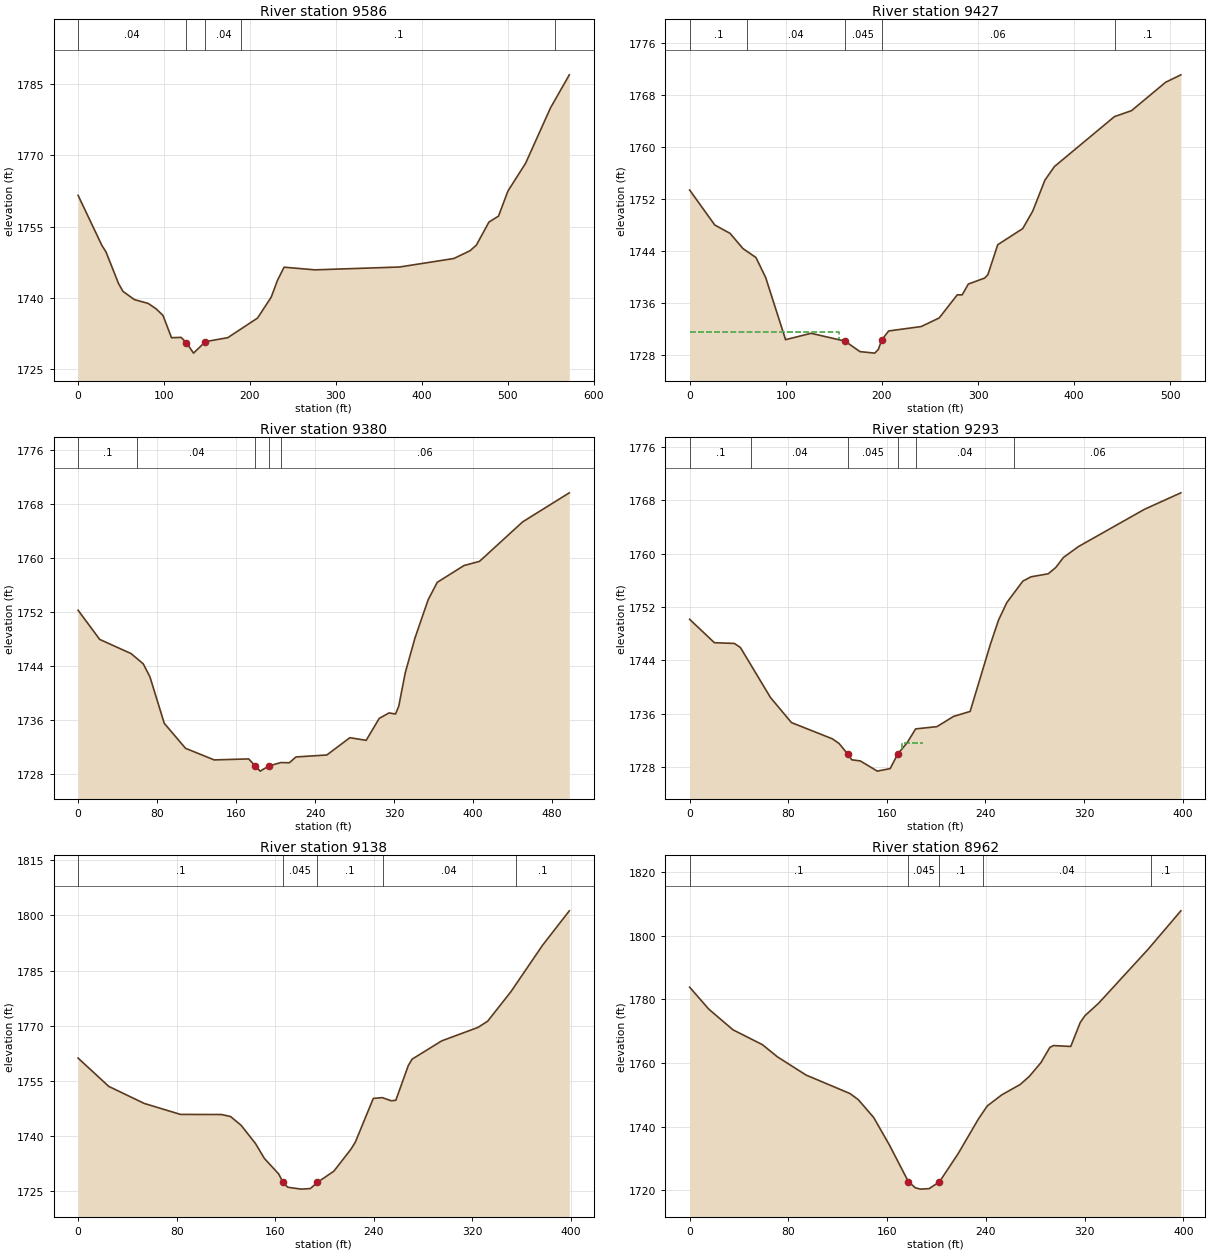
Type RM Length L Ch R = 1 ,9586    ,94.3,159.3,188.4
XS GIS Cut Line= 4
2040840.38948886216979.4342528682040912.01012883216944.252184114
2041089.17697505216861.3230220512041353.04249071216726.877259312
#Sta/Elev= 30
       0  1761.6    27.6 1751.08    32.5 1749.66    47.1    1743    52.2 1741.37
    65.4 1739.64    81.6 1738.82    90.9 1737.67    98.8 1736.29   108.7  1731.6
   119.8 1731.67     126 1730.57   134.3 1728.35   148.2 1730.77   174.2 1731.61
   208.8 1735.74   224.7 1740.14   232.1 1743.73   239.7 1746.46   275.6  1745.9
   374.1  1746.5   437.2 1748.29     456 1749.92   463.4  1751.1   478.1 1755.97
   489.2 1757.22   500.2 1762.52   520.7 1768.35   549.7 1780.03   571.6    1787
#Mann= 5 ,-1 , 0
       0     .04       0     126    .045       0   148.2     .04       0
   189.8      .1       0  555.41     .06       0
Bank Sta=126,148.2
XS Rating Curve= 0 ,0
Exp/Cntr(USF)=0,0
Exp/Cntr=0.5,0.3

Type RM Length L Ch R = 1 ,9427    ,75.2,47.1,109.9
XS GIS Cut Line= 4
2040884.36707481217030.9508535442041007.50431545217002.051297067
2041097.97249224217152.831591727 2041305.2953974217176.705138382
#Sta/Elev= 30
       0 1753.36    26.1 1747.98    42.1 1746.68    55.5 1744.34      69 1742.97
    79.1 1739.89    99.8 1730.33   126.3 1731.31   161.6 1730.11   177.2 1728.49
   192.6 1728.26   196.3 1728.83   199.8 1730.28     207 1731.67   240.9 1732.35
   259.6 1733.67   278.4 1737.23   283.5 1737.22   289.9 1738.89   306.9 1739.81
   310.2 1740.31   320.5 1744.94   346.5 1747.42   356.9 1750.11   369.6 1754.88
   379.5 1756.97   441.9 1764.65   459.7 1765.57   495.1 1769.93     511 1771.08
#Mann= 5 ,-1 , 0
       0      .1       0      60     .04       0   161.6    .045       0
   199.8     .06       0  442.32      .1       0
#XS Ineff= 2 , 0
             155 1731.51
Permanent Ineff=
       F       F
Bank Sta=161.6,199.8
XS Rating Curve= 0 ,0
Exp/Cntr(USF)=0,0
Exp/Cntr=0.5,0.3

Type RM Length L Ch R = 1 ,9380    ,100.9,86.8,15.1
XS GIS Cut Line= 5
2040887.76202917217042.0887045762040972.22025132217020.163943933
2041038.86251138217117.6530761212041059.29421236217180.445425101
2041283.93485566217205.604694858
#Sta/Elev= 30
       0 1752.28   21.86 1747.96   53.64 1745.86   65.92 1744.35    72.7 1742.44
   87.26 1735.53   108.8 1731.83  137.86 1730.11  172.75 1730.26  179.44 1729.21
  184.37 1728.45  193.25 1729.22  205.35 1729.72  213.91 1729.69  220.64 1730.55
  251.88 1730.84  275.23  1733.4  291.73 1733.01  304.94 1736.26  314.84 1737.07
  321.44 1736.91  324.75 1738.09  331.35 1743.05  341.17 1748.18  354.46 1753.82
  363.66 1756.41  390.77  1758.9  406.49 1759.52   450.2 1765.37  497.43 1769.67
#Mann= 5 ,-1 , 0
       0      .1       0      60     .04       0  179.44    .045       0
  193.25     .04       0  205.35     .06       0
Bank Sta=179.44,193.25
XS Rating Curve= 0 ,0
Exp/Cntr(USF)=0,0
Exp/Cntr=0.5,0.3

Type RM Length L Ch R = 1 ,9293    ,151.5,155.3,157.8
XS GIS Cut Line= 4
2040894.28178755217124.4127739612040977.63690394217166.548327304
2041091.21969991217204.103929197 2041276.2497385217218.759773838
#Sta/Elev= 30
       0 1750.14    20.1 1746.63    36.3 1746.52    41.2 1745.91    65.6  1738.4
    82.6 1734.64   115.8  1732.2   121.2 1731.51  128.21 1729.93   131.6 1729.05
   138.5 1728.88   152.3 1727.35   162.7 1727.73  168.921729.929   176.5 1731.62
   183.4 1733.69   200.7 1734.03   214.1 1735.56   227.6 1736.31   244.1 1746.42
   250.7 1750.05   257.4 1752.66   270.4 1755.88     277 1756.52     291 1756.98
   297.1 1757.92   303.3 1759.42   315.4 1761.05   369.1 1766.66   398.6 1769.13
#Mann= 6 ,-1 , 0
       0      .1       0      50     .04       0  128.21    .045       0
  168.92     .06       0   183.4     .04       0  263.03     .06       0
#XS Ineff= 2 ,-1
172.5062188.9782 1731.51365.6248373.4366 1731.51
Permanent Ineff=
       T       T
Bank Sta=128.21,168.92
XS Rating Curve= 0 ,0
Exp/Cntr(USF)=0,0
Exp/Cntr=0.3,0.1

Type RM Length L Ch R = 1 ,9138    ,171.9,176.5,179.7
XS GIS Cut Line= 4
2040836.57439927217226.087696158 2040953.8211564217314.938754294
2041050.91612715217362.5702493782041177.32278718217430.353530842
#Sta/Elev= 30
       0 1761.22    24.9 1753.53    53.7  1748.9    83.1 1745.92   116.4 1745.89
   123.7 1745.35   132.3 1742.97     144    1738   151.2 1733.96   162.9 1729.71
  166.281727.466   170.2 1726.13   181.1 1725.62   188.5 1725.77  194.311727.469
   207.6  1730.5   221.3 1736.39     225 1738.37   239.6 1750.26   246.9 1750.48
   254.2 1749.62   257.9 1749.77     268 1759.19   271.1 1760.93   295.2 1765.91
   324.4 1769.53   332.4 1771.23   351.3 1779.26   377.1 1791.93   398.7 1801.23
#Mann= 5 ,-1 , 0
       0      .1       0  166.28    .045       0  194.31      .1       0
  247.11     .04       0  355.26      .1       0
Bank Sta=166.28,194.31
XS Rating Curve= 0 ,0
Exp/Cntr(USF)=0,0
Exp/Cntr=0.3,0.1

Type RM Length L Ch R = 1 ,8962    ,202.5,198.6,195.5
XS GIS Cut Line= 4
2040722.07561302217361.6542590882040820.08657405217426.689569682
2040923.59347683217498.1368123072041059.16003976217572.332025802
#Sta/Elev= 30
       0 1783.85    15.5 1776.95    35.2 1770.43    58.9  1765.8    71.1 1761.96
    94.3 1756.24   129.9 1750.42   136.6 1748.51   149.1 1742.89   161.8 1734.27
  177.251722.694   182.8 1720.83   186.9 1720.39     194 1720.55  202.361722.693
   217.5 1731.54     234 1742.48   241.1 1746.53   252.8 1750.01   267.8 1753.28
   275.3 1755.88   284.6 1760.16   291.8 1764.93   294.7  1765.5   308.7 1765.22
   316.4 1772.76   320.2 1774.88   331.4 1778.85   371.6 1795.86   397.9 1807.84
#Mann= 5 ,-1 , 0
       0      .1       0  177.25    .045       0  202.36      .1       0
  237.63     .04       0   373.4      .1       0
Bank Sta=177.25,202.36
XS Rating Curve= 0 ,0
Exp/Cntr(USF)=0,0
Exp/Cntr=0.3,0.1

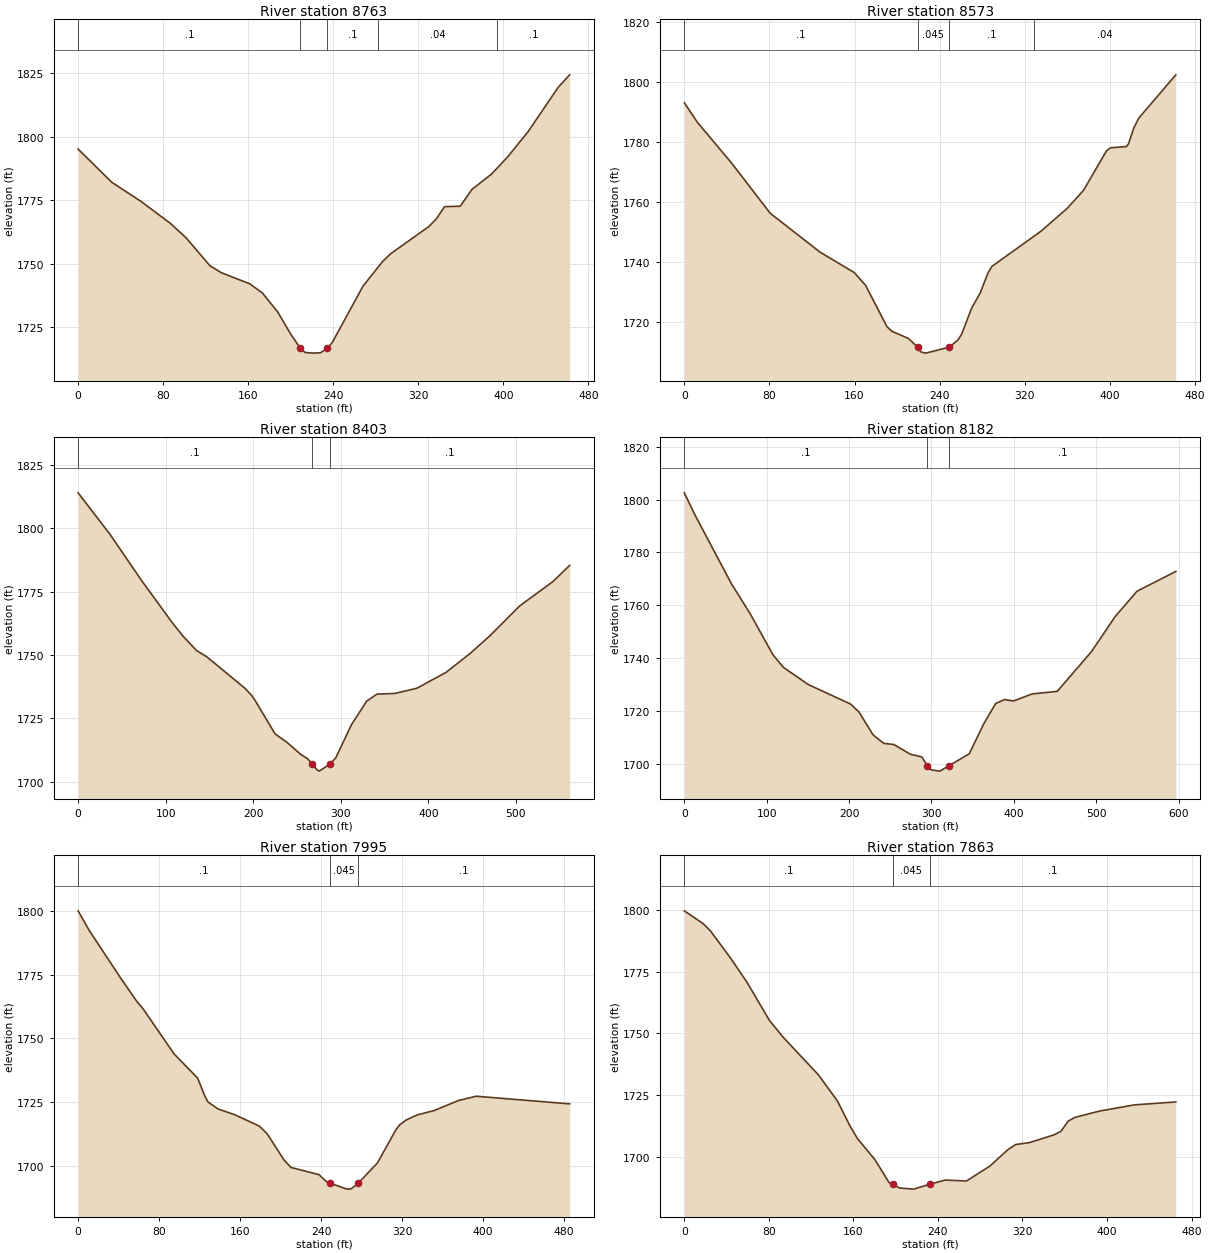
Type RM Length L Ch R = 1 ,8763    ,182.3,189.8,196.8
XS GIS Cut Line= 4
2040591.45785481217534.4800289412040749.21871867217625.227428505
 2040877.6611919217686.6564374412041000.51920977217749.481560216
#Sta/Elev= 30
       0  1795.1    31.7 1782.03    59.7 1774.36      87  1765.8   101.4 1760.28
     124 1749.21     135 1746.42   161.5 1742.09   173.5 1738.44   187.9 1730.94
   200.3 1722.09  209.151716.723   213.6 1715.07   220.8 1714.83   228.1 1714.98
  234.211716.727     239 1718.96   268.1 1741.23   286.4 1750.84   293.8 1753.86
     330 1764.64   337.4 1767.85   344.7 1772.45   359.5 1772.61   370.5 1779.23
     389  1785.3   403.8 1791.87   423.3 1801.94   451.6 1819.36   462.4  1824.3
#Mann= 5 ,-1 , 0
       0      .1       0  209.15    .045       0  234.21      .1       0
     282     .04       0  394.38      .1       0
Bank Sta=209.15,234.21
XS Rating Curve= 0 ,0
Exp/Cntr(USF)=0,0
Exp/Cntr=0.3,0.1

Type RM Length L Ch R = 1 ,8573    ,165.3,169.7,175.7
XS GIS Cut Line= 4
2040506.29491061217630.8118838632040631.94515616217752.273787895
2040721.29644188217837.4367321022040848.34280127217940.749156221
#Sta/Elev= 30
       0 1792.99    12.4 1786.44    44.4 1772.94    80.7 1756.22   127.8 1743.21
   159.6  1736.5   170.3 1732.25   190.3 1718.56   194.8 1716.98   210.7 1714.52
  219.191711.643   222.5 1710.01   226.9 1709.65  249.021711.645   257.1    1714
   260.6 1715.93   270.1 1724.69     278 1729.62   285.4 1736.35   289.1 1738.53
   335.1 1750.22   359.5 1757.74   375.1 1763.82   396.8 1777.03   400.5 1778.02
   415.5 1778.43   417.4  1779.3   422.4 1784.59   427.1  1787.9   461.9  1802.3
#Mann= 4 ,-1 , 0
       0      .1       0  219.19    .045       0  249.02      .1       0
   328.2     .04       0
Bank Sta=219.19,249.02
XS Rating Curve= 0 ,0
Exp/Cntr(USF)=0,0
Exp/Cntr=0.3,0.1

Type RM Length L Ch R = 1 ,8403    ,216.6,221.1,225.5
XS GIS Cut Line= 4
2040379.24855122217660.1302744922040483.95708918 217815.09891067
 2040580.2889441217956.1064084552040707.33530349218115.263386152
#Sta/Elev= 30
       0 1814.06    36.2 1797.79    72.3 1779.53   107.4 1762.86   119.8 1757.48
   135.2 1751.84     147 1749.32   190.4 1736.96   198.6 1733.92   202.5 1731.91
     225 1718.88   238.3 1715.65   254.1 1710.85   262.1 1709.11  267.351707.035
     273 1704.65   275.4  1704.2  287.921707.036   294.3 1709.44   312.2 1722.53
   329.6 1731.83   341.3 1734.59   361.7 1734.86   386.9 1736.92   420.4 1743.22
   448.1 1750.76   470.1 1757.55   504.4 1769.43   542.2 1779.01   561.4  1785.4
#Mann= 3 ,-1 , 0
       0      .1       0  267.35    .045       0  287.92      .1       0
Bank Sta=267.35,287.92
XS Rating Curve= 0 ,0
Exp/Cntr(USF)=0,0
Exp/Cntr=0.3,0.1

Type RM Length L Ch R = 1 ,8182    ,169.5,187.5,203.3
XS GIS Cut Line= 4
 2040268.9555579217713.1826003912040323.40399764217949.125839257
2040383.43689274218088.7372232022040483.95708918218264.647566973
#Sta/Elev= 30
       0 1802.56    13.3 1793.97    57.1 1768.21    80.7 1756.42   107.6 1741.28
   120.4 1736.48   150.5 1730.01   201.9 1722.61     212 1719.65   228.8 1711.13
   232.2 1710.19   242.3 1707.74   254.3 1707.32   274.5 1703.62   288.4  1702.6
   294.91699.288   299.5 1697.74   310.2 1697.24  321.291699.289   345.9  1703.8
   363.7 1715.24     378 1722.83   388.7 1724.32   399.8  1723.8   422.4 1726.47
   452.7 1727.42   494.3 1742.47   523.2  1755.8   549.6 1765.32   596.7 1772.82
#Mann= 3 ,-1 , 0
       0      .1       0   294.9    .045       0  321.29      .1       0
Bank Sta=294.9,321.29
XS Rating Curve= 0 ,0
Exp/Cntr(USF)=0,0
Exp/Cntr=0.3,0.1

Type RM Length L Ch R = 1 ,7995    ,139,131.8,111.8
XS GIS Cut Line= 4
2040245.22162263217718.7670557482040213.11100432217873.735691927
 2040162.8509061218024.5159865882040112.59080788218185.069078124
#Sta/Elev= 30
       0 1800.17    10.9 1792.51    41.5 1774.04    57.8 1764.65    64.5 1761.47
    94.7 1743.94   118.1 1734.38   124.8 1727.65   128.2 1725.03   138.2 1722.28
     155 1719.96   179.1  1715.5   186.7  1712.5   203.3 1702.26   210.2 1699.28
   237.9 1696.45   244.8 1693.85  248.691693.118   265.6 1690.76   269.6 1690.86
  276.711693.118   295.6 1701.07   313.7 1714.01   317.4 1715.98   324.2 1717.99
   334.8 1719.93   351.8 1721.68   375.9 1725.64   393.1 1727.28   485.4 1724.28
#Mann= 3 ,-1 , 0
       0      .1       0  248.69    .045       0  276.71      .1       0
Bank Sta=248.69,276.71
XS Rating Curve= 0 ,0
Exp/Cntr(USF)=0,0
Exp/Cntr=0.3,0.1

Type RM Length L Ch R = 1 ,7863    ,185.1,174.9,145.3
XS GIS Cut Line= 4
2040013.46672528217718.7670557482040051.16179895217855.586212014
2040080.48018958218023.1198727482040097.23355565218175.296281248
#Sta/Elev= 30
       0 1799.69    17.9 1794.48    24.7 1791.56    43.2 1780.87    59.2 1770.81
    80.6 1755.21    93.9 1748.27   126.8 1733.23   144.8 1722.63   157.1  1712.2
   163.8 1707.37   180.4 1698.76   193.7 1689.53  197.311688.847   203.7 1687.28
   217.1 1686.83  232.451688.845     247 1690.51     267 1690.13   289.3 1696.21
   306.3 1702.89   313.6 1704.92   326.9 1705.72   349.9 1708.86   356.5 1710.31
   363.1 1714.36   369.7 1715.94   392.8 1718.47   425.9    1721   465.1 1722.19
#Mann= 3 ,-1 , 0
       0      .1       0  197.31    .045       0  232.45      .1       0
Bank Sta=197.31,232.45
XS Rating Curve= 0 ,0
Exp/Cntr(USF)=0,0
Exp/Cntr=0.3,0.1

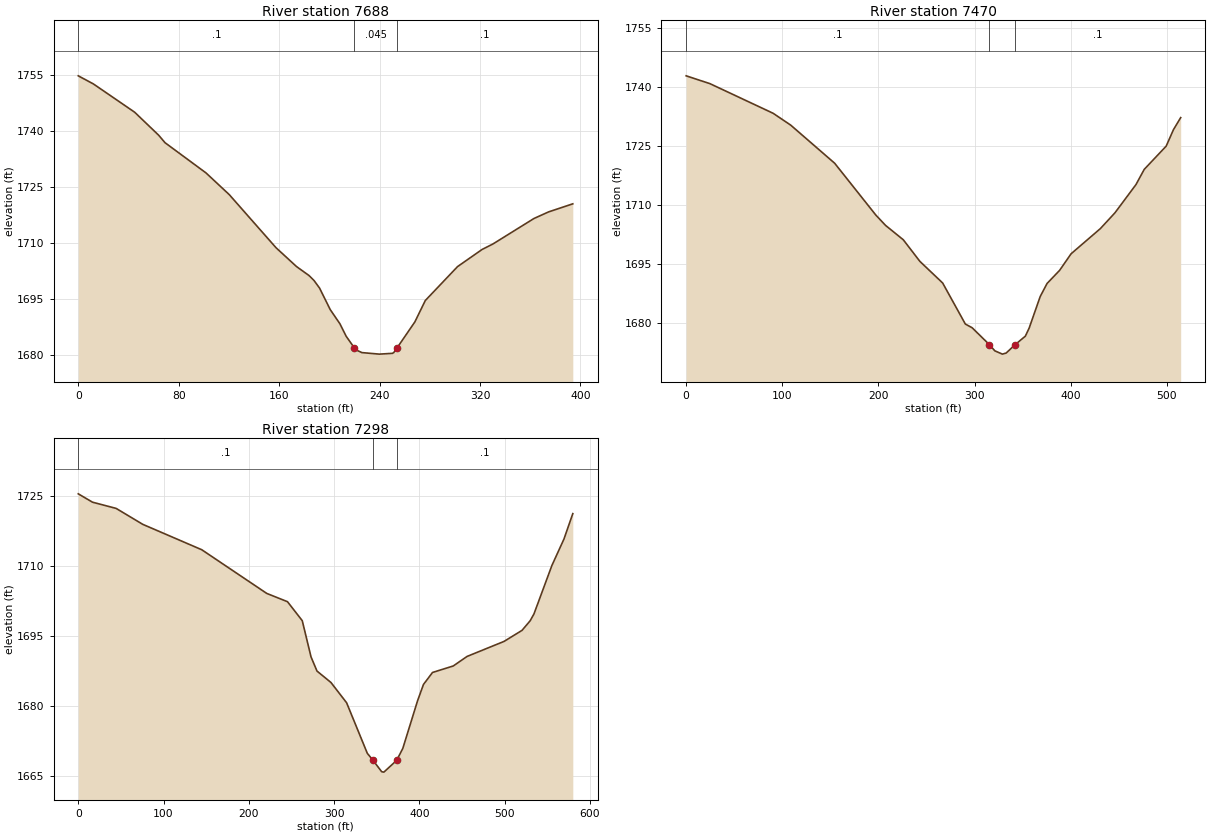
Type RM Length L Ch R = 1 ,7688    ,213.7,218.1,224.9
XS GIS Cut Line= 4
2039816.61467392217887.6968303222039931.09600876218020.327645069
  2040024.635636  218095.7177924 2040084.6685311218173.900167409
#Sta/Elev= 30
       0 1754.85      12 1752.69    44.9 1745.11      64 1738.96    69.1 1736.94
   101.7 1728.86   120.2 1723.06   157.5 1708.82   173.8 1703.78   183.8 1701.37
   187.8 1700.03   192.2    1698   200.7 1692.24   208.4 1688.45   213.4 1685.09
  219.831682.027   221.7 1681.38   225.9 1680.73   239.8 1680.32   250.2 1680.53
   251.2 1680.71  254.011682.031   268.1 1688.95   276.4 1694.67   302.1 1703.76
   321.7 1708.36   330.2  1709.8     363 1716.65   374.7 1718.42   393.9 1720.57
#Mann= 3 ,-1 , 0
       0      .1       0  219.83    .045       0  254.01      .1       0
#XS Ineff= 2 , 0
                        388.7646         1697.48
Permanent Ineff=
       F       T
Bank Sta=219.83,254.01
XS Rating Curve= 0 ,0
Exp/Cntr(USF)=0,0
Exp/Cntr=0.3,0.1

Type RM Length L Ch R = 1 ,7470    ,167,172.4,178.9
XS GIS Cut Line= 4
2039709.11390828217953.3141807762039806.84187704218152.958459817
2039907.36207349218300.946526798 2039964.6027409 218398.67449556
#Sta/Elev= 30
       0 1742.84    24.7 1740.86    90.5 1733.33   108.8 1730.32   154.5 1720.65
   197.3  1707.5   207.4 1704.88   225.9 1701.22   243.1 1695.75   266.8 1690.26
   290.4 1679.84   297.5 1678.89  315.521674.584   321.1 1673.03     329  1672.2
   332.9 1672.48  342.081674.582   352.8 1676.75   356.8 1678.82   368.3 1686.83
   375.4 1690.13   388.5 1693.47   400.4 1697.67   430.9 1704.07   446.1 1708.09
   467.9 1715.24   476.5  1719.1   499.3 1724.99   506.9 1729.18   514.4 1732.23
#Mann= 3 ,-1 , 0
       0      .1       0  315.52    .045       0  342.08      .1       0
Bank Sta=315.52,342.08
XS Rating Curve= 0 ,0
Exp/Cntr(USF)=0,0
Exp/Cntr=0.3,0.1

Type RM Length L Ch R = 1 ,7298    ,182.9,196.6,208
XS GIS Cut Line= 4
2039604.40537032217982.6325714042039686.77608685218226.952493308
2039739.82841275218381.9211294862039795.67296633218529.909196468
#Sta/Elev= 30
       0 1725.49    16.7  1723.7    44.4 1722.37    75.6 1718.96   144.8 1713.52
     221 1704.17   245.3  1702.4   262.6 1698.34   272.9 1690.58   279.9 1687.55
   296.3  1685.1   314.6 1680.77   338.9 1669.94  345.631668.434   355.7 1666.01
   358.3 1665.92   373.31668.435   380.5    1671   397.8  1681.2   404.7 1684.68
   415.3 1687.25   439.6 1688.64   455.9 1690.69   499.2  1693.9   520.3 1696.27
   529.8 1698.32   534.3  1699.8   555.3 1710.16   569.4  1715.8   579.8 1721.25
#Mann= 3 ,-1 , 0
       0      .1       0  345.63    .045       0   373.3      .1       0
Bank Sta=345.63,373.3
XS Rating Curve= 0 ,0
Exp/Cntr(USF)=0,0
Exp/Cntr=0.3,0.1