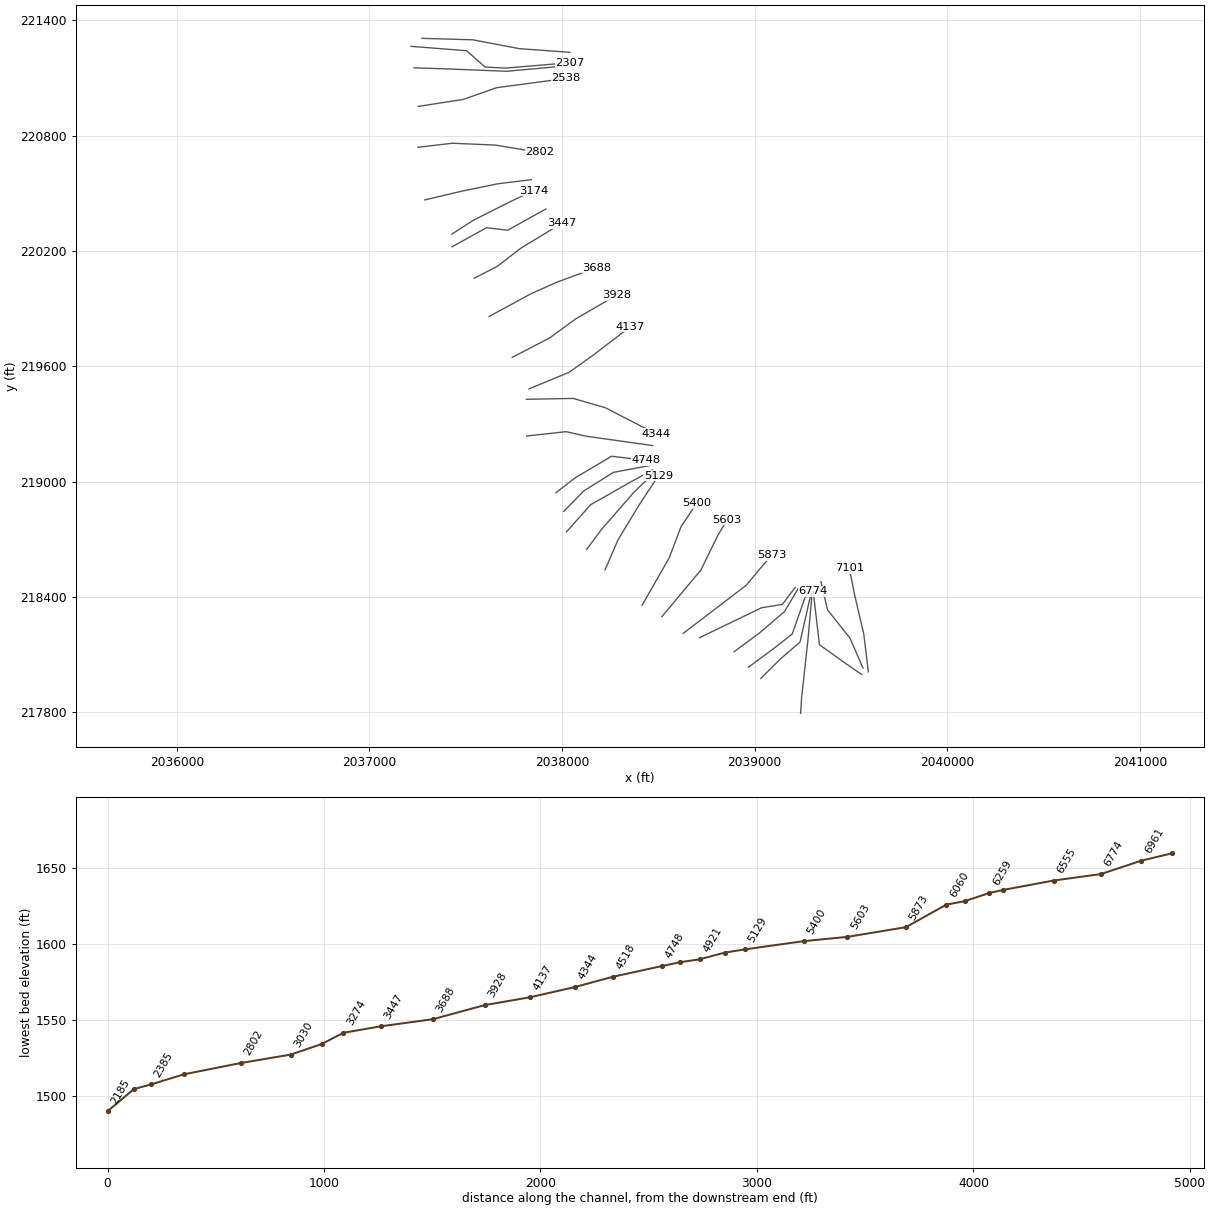
HEC-RAS study LTLSTNYCK.prj: LTLSTNYCK

--- LTLSTNYCK.g01 (geometry) --- (continued)

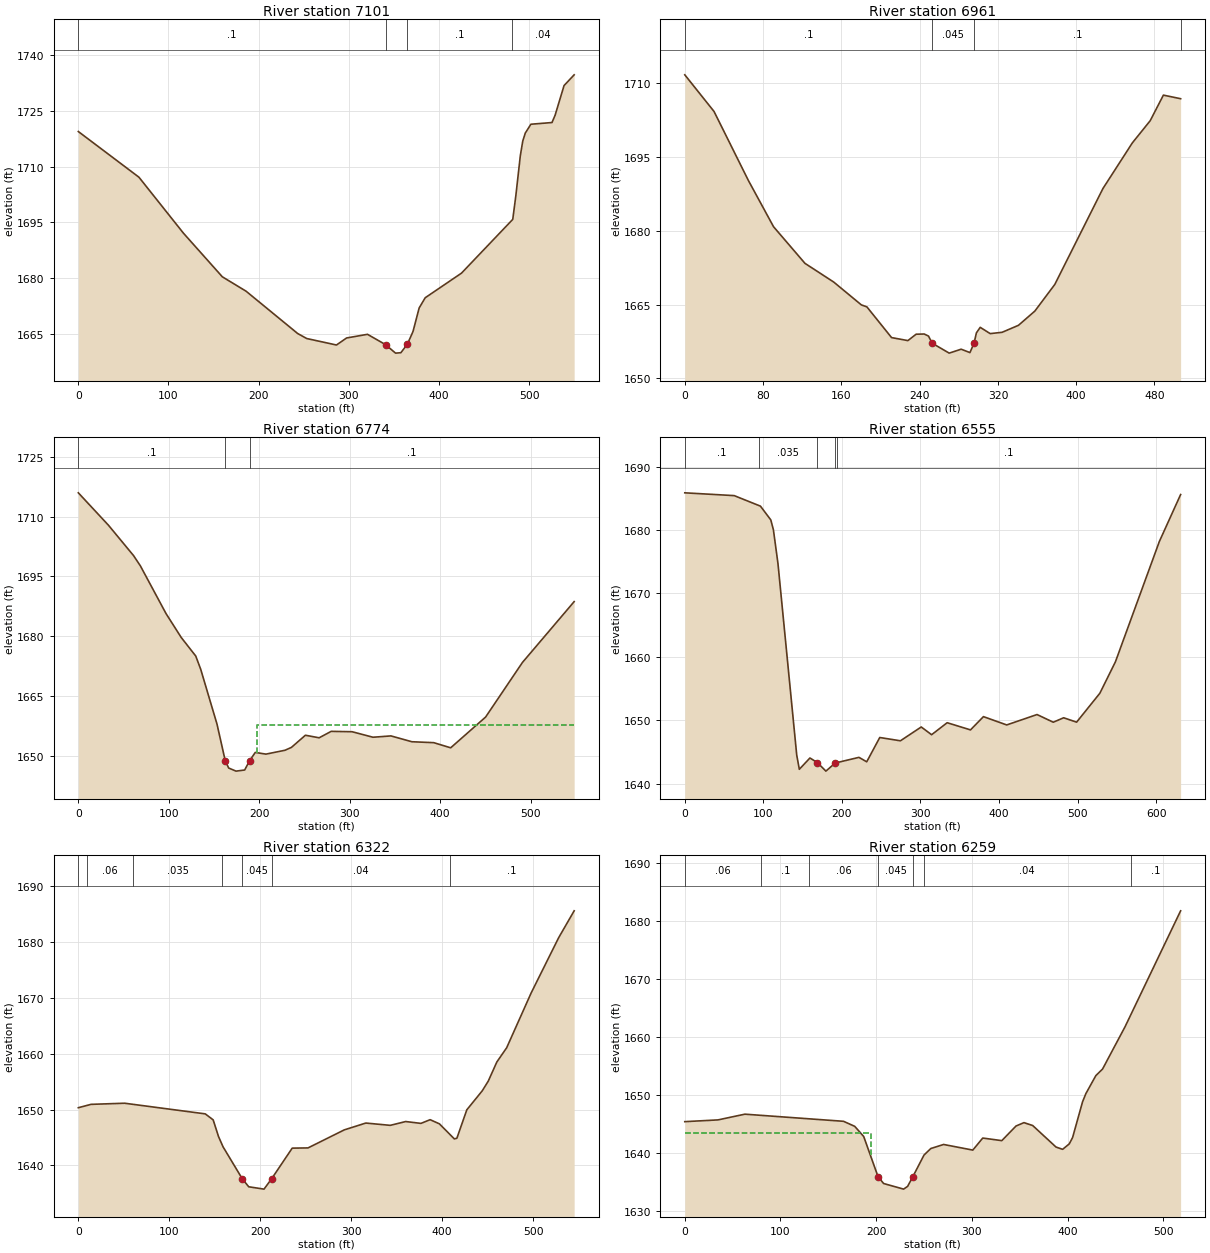
Type RM Length L Ch R = 1 ,7101    ,134.2,140.1,147.4
XS GIS Cut Line= 4
2039590.44423193218010.5548481932039566.71029666218207.406899555
2039520.63853996218404.2589509182039491.32014933 218550.85090406
#Sta/Elev= 30
       0 1719.41    67.2 1707.15   116.7 1692.08   159.7  1680.4   186.1 1676.52
   243.2 1665.18   253.3 1663.82   286.3 1662.08   297.5 1663.97   320.7 1664.95
   340.9 1662.16   340.9 1662.15   340.9 1662.14   351.8  1659.9   357.7 1660.01
  364.881662.274   371.2 1665.72     378 1672.03   384.7 1674.77     425 1681.39
   481.8 1695.82   485.2 1702.13   490.2 1712.92   492.9 1716.85   495.7 1718.99
   501.9 1721.37   525.3 1721.83   528.7 1723.74   538.7 1731.76   549.9 1734.64
#Mann= 4 ,-1 , 0
       0      .1       0   340.9    .045       0  364.88      .1       0
  480.45     .04       0
Bank Sta=340.9,364.88
XS Rating Curve= 0 ,0
Exp/Cntr(USF)=0,0
Exp/Cntr=0.3,0.1

Type RM Length L Ch R = 1 ,6961    ,156.9,187.3,184.3
XS GIS Cut Line= 4
2039562.52195514218030.1004419452039495.50849085218185.069078124
2039378.23492833218333.0571451062039344.72819619218478.252984408
#Sta/Elev= 30
       0 1711.74    29.9 1704.28    64.8 1690.31    90.7 1680.83   122.8 1673.38
   152.2 1669.57   180.4 1664.93   186.1 1664.52   211.3 1658.27     228 1657.66
   236.4 1658.96   244.7    1659   249.1 1658.57  252.771657.132   270.2 1655.11
   282.4 1655.91   291.4 1655.22  295.581657.132     298 1659.23   301.9 1660.36
   312.1 1659.08   324.3 1659.35     341 1660.77   357.7 1663.66   378.1 1669.08
   427.3  1688.6   457.4  1697.9   475.6  1702.4   489.1 1707.61   506.7 1706.88
#Mann= 4 ,-1 , 0
       0      .1       0  252.77    .045       0  295.58      .1       0
  506.67     .04       0
Bank Sta=252.77,295.58
XS Rating Curve= 0 ,0
Exp/Cntr(USF)=0,0
Exp/Cntr=0.3,0.1

Type RM Length L Ch R = 1 ,6774    ,234.6,218.3,188.8
XS GIS Cut Line= 4
2039555.54138594217996.5937097992039474.56678326218052.438263377
2039336.35151315218151.5623459772039304.24089484218429.389000028
#Sta/Elev= 30
       0 1715.95    33.2 1707.86    61.1 1700.21    68.6 1697.65    96.9 1685.72
   113.7 1679.73   129.8 1675.07   135.3 1671.74   153.3 1658.01  162.391648.852
   166.2 1647.02   174.3 1646.24   183.9 1646.52  189.311648.852   195.6 1650.92
   207.4  1650.5   228.5 1651.47   235.6 1652.19     251 1655.23   266.2 1654.59
   279.5  1656.2   302.6 1656.11   325.7 1654.73   345.6 1655.06   368.7  1653.6
   392.9 1653.37   411.6 1652.08   450.2 1659.78   490.9 1673.45   548.1  1688.7
#Mann= 3 ,-1 , 0
       0      .1       0  162.39    .045       0  189.31      .1       0
#XS Ineff= 2 , 0
                           197.6         1657.73
Permanent Ineff=
       F       F
Bank Sta=162.39,189.31
XS Rating Curve= 0 ,0
Exp/Cntr(USF)=0,0
Exp/Cntr=0.3,0.1

Type RM Length L Ch R = 1 ,6555    ,234.4,233.1,207.5
XS GIS Cut Line= 4
2039238.62354439217794.1572030792039244.20799975217877.924033446
2039277.71473189218185.0690781242039298.65643949218422.408430831
#Sta/Elev= 30
       0 1685.85    62.9 1685.41    96.3 1683.75   109.5 1681.58   112.8 1680.02
   118.6 1674.72   142.5  1644.5   145.8 1642.27   159.3 1644.05   168.9 1643.32
   179.6 1641.98   191.5 1643.26   221.7 1644.15   231.6 1643.45   248.2 1647.28
   274.5 1646.76     301 1648.94   314.2 1647.72     334 1649.61   363.7 1648.48
   380.2 1650.57   409.8 1649.26   448.4  1650.9   469.1 1649.69   482.3 1650.39
   498.8  1649.7   528.4 1654.26   548.2 1659.21   604.1 1678.17   631.2 1685.58
#Mann= 5 ,-1 , 0
       0      .1       0   93.95    .035       0   168.9    .045       0
   191.5    .035       0  193.95      .1       0
Bank Sta=168.9,191.5
XS Rating Curve= 0 ,0
Exp/Cntr(USF)=0,0
Exp/Cntr=0.5,0.3

Type RM Length L Ch R = 1 ,6322    ,65.8,63.3,61.9
XS GIS Cut Line= 4
2039031.99869615217975.6520022072039129.72666491218073.379970968
2039235.83131671218165.5234843722039294.46809797218425.200658509
#Sta/Elev= 30
       0 1650.32      14 1650.92    50.9 1651.12   139.5 1649.22   148.2 1648.15
   154.1 1645.17   159.1 1643.33  180.161637.637   187.3  1636.2   204.1 1635.78
  212.511637.639   235.1  1643.1   252.5 1643.14   292.3 1646.36     316 1647.58
   342.9 1647.17   359.8 1647.85   376.6 1647.52   386.7 1648.18   396.9 1647.44
   413.3 1644.75   416.1 1644.87     427 1649.94   443.9 1653.32   450.6 1655.07
     460 1658.48   470.8 1661.02   497.7  1670.8   527.9 1680.66     545 1685.48
#Mann= 7 ,-1 , 0
       0    .035       0      10     .06       0      60    .035       0
  158.21     .06       0  180.16    .045       0  212.51     .04       0
  408.74      .1       0
Bank Sta=180.16,212.51
XS Rating Curve= 0 ,0
Exp/Cntr(USF)=0,0
Exp/Cntr=0.5,0.3

Type RM Length L Ch R = 1 ,6259    ,115.7,114.5,115.4
XS GIS Cut Line= 4
2038967.77745954218034.2887834642039096.21993277218129.224524546
2039195.34401537218207.4068995552039272.13027654218426.596772349
#Sta/Elev= 30
       0 1645.41    34.6 1645.71    62.8  1646.7   165.9 1645.47   177.6  1644.6
     187 1642.84  201.981635.905   207.8 1634.73   228.7 1633.76   232.9 1634.24
  238.321635.907     250 1639.64   257.1 1640.77   270.5 1641.47     301  1640.5
   311.4 1642.58   331.3 1642.13   346.2 1644.66   354.5 1645.24   363.6 1644.74
     388 1641.02   394.9 1640.63   401.8 1641.57   405.3 1642.67   415.7 1648.83
   419.2 1650.26   429.6 1653.36   436.6 1654.49   460.1 1661.79   518.2 1681.81
#Mann= 7 ,-1 , 0
       0     .06       0      80      .1       0     130     .06       0
  201.98    .045       0  238.32     .06       0  249.72     .04       0
  465.97      .1       0
#XS Ineff= 2 , 0
             195 1643.46
Permanent Ineff=
       F       F
Bank Sta=201.98,238.32
XS Rating Curve= 0 ,0
Exp/Cntr(USF)=0,0
Exp/Cntr=0.5,0.3

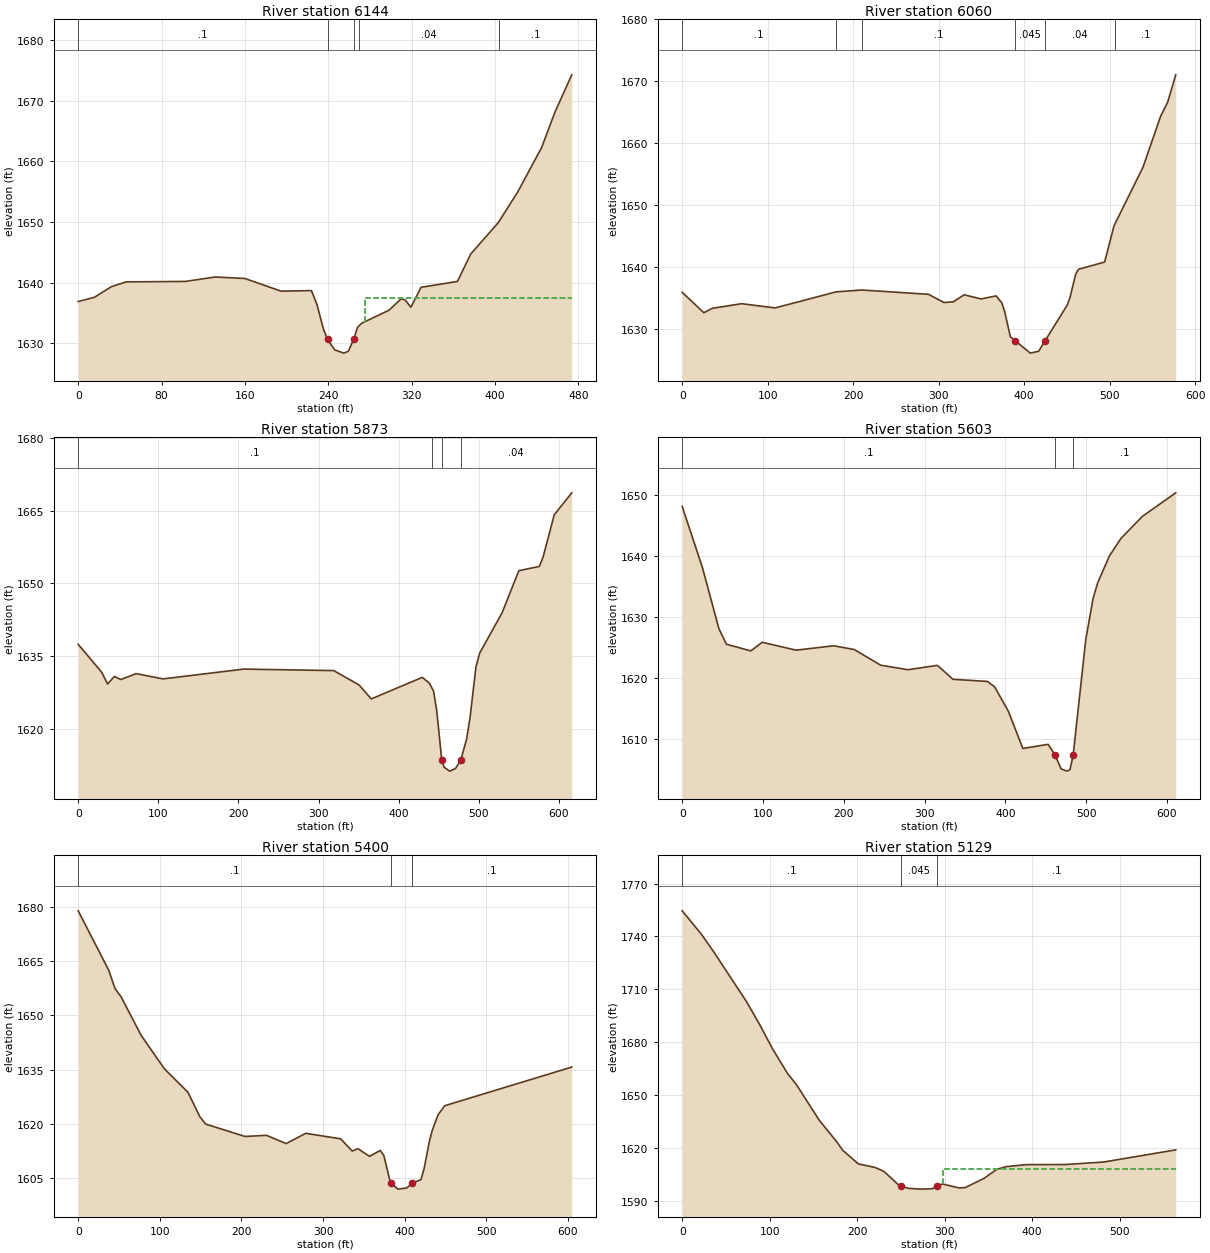
Type RM Length L Ch R = 1 ,6144    ,95.2,84.1,72.1
XS GIS Cut Line= 4
2038893.78342605218115.2633861522039022.22589928218210.199127234
2039154.85671402 218323.284348232039226.05851983218443.350138422
#Sta/Elev= 30
       0 1636.87    15.5 1637.57      32 1639.34      46 1640.11   102.9 1640.19
   131.4 1640.92     160 1640.67   194.5 1638.59   223.8 1638.67     229 1636.42
   235.4 1632.28   239.21630.615   246.2 1628.89   254.9 1628.36   259.2 1628.67
  264.271630.615     268 1632.61   272.1  1633.3   298.3 1635.45   309.9 1637.32
   313.8 1637.11   319.2 1635.93     329 1639.22   363.9 1640.19   376.7 1644.73
   403.1 1649.89   421.8 1654.97   444.7 1662.29   457.7 1668.22   473.6 1674.27
#Mann= 5 ,-1 , 0
       0      .1       0   239.2    .045       0  264.27      .1       0
  269.72     .04       0  404.02      .1       0
#XS Ineff= 2 , 0
                          275.07         1637.48
Permanent Ineff=
       F       T
Bank Sta=239.2,264.27
XS Rating Curve= 0 ,0
Exp/Cntr(USF)=0,0
Exp/Cntr=0.3,0.1

Type RM Length L Ch R = 1 ,6060    ,170.9,187,204.9
XS GIS Cut Line= 4
 2038713.9971332218187.8221418422039036.29001303218343.879746815
2039143.72097298218360.8425299642039210.44125337218449.049002341
#Sta/Elev= 30
       0 1635.91    25.3 1632.61    35.1 1633.32    69.5 1634.07   108.8 1633.39
     180 1635.98     210 1636.28   288.1 1635.59   306.2 1634.26   317.2 1634.38
   329.9 1635.51   349.5 1634.84   367.3 1635.33     374 1634.17   377.3 1632.77
   383.9 1628.73  389.56  1628.1   407.2 1626.09   417.1  1626.4  424.58  1628.1
   450.4 1633.84   453.7 1635.08   460.3 1638.84   463.6 1639.62   494.2  1640.8
   505.1 1646.62   539.1 1656.12   559.5 1664.27   567.9  1666.6   577.4 1671.02
#Mann= 6 ,-1 , 0
       0      .1       0     180    .035       0     210      .1       0
  389.56    .045       0  424.58     .04       0  506.85      .1       0
Bank Sta=389.56,424.58
XS Rating Curve= 0 ,0
Exp/Cntr(USF)=0,0
Exp/Cntr=0.3,0.1

Type RM Length L Ch R = 1 ,5873    ,266,270.8,276
XS GIS Cut Line= 4
2038629.18321745218210.4391860412038955.99950613 218460.35752444
2039022.71978652218540.6480313472039088.30921469218616.415129414
#Sta/Elev= 30
       0 1637.41    29.2 1631.68    36.6 1629.21    45.1 1630.78    53.1 1630.14
    72.4 1631.36   105.9 1630.27   206.6  1632.3   318.9 1631.99   350.5 1629.02
   365.7 1626.13   429.4 1630.59   438.4 1629.37   443.5 1627.73   447.5 1623.63
  453.741613.436   456.8 1611.99   463.6  1611.2   470.8 1611.73  477.391613.441
   484.8 1617.88   489.2 1622.51   496.4 1632.77   501.1 1635.62     529 1643.93
   549.9 1652.65   575.5 1653.53   580.2 1655.48   594.1  1664.2     616 1668.75
#Mann= 4 ,-1 , 0
       0      .1       0  441.42     .04       0  453.74    .045       0
  477.39     .04       0
Bank Sta=453.74,477.39
XS Rating Curve= 0 ,0
Exp/Cntr(USF)=0,0
Exp/Cntr=0.3,0.1

Type RM Length L Ch R = 1 ,5603    ,200.3,202.2,203.5
XS GIS Cut Line= 4
2038518.35970088218297.5148062072038720.78224646218539.517179137
2038806.72701441 218715.930123892038856.48451165218801.874891846
#Sta/Elev= 30
       0 1648.12    25.1 1638.09    45.4 1628.13    54.7 1625.57      85 1624.47
      99 1625.89   140.9 1624.59   187.6 1625.31   213.1 1624.69   245.7 1622.13
   279.4 1621.39   315.9  1622.1   335.2 1619.82   377.9 1619.47   386.8 1618.57
   403.9 1614.55   421.7 1608.49     453 1609.17  461.331607.461   469.1 1605.14
   476.4 1604.78   480.1 1605.04  484.031607.461   499.6 1626.34   508.7 1633.09
   514.3 1635.61   528.7 1639.99   543.1 1642.89   569.8 1646.52     611 1650.36
#Mann= 3 ,-1 , 0
       0      .1       0  461.33    .045       0  484.03      .1       0
Bank Sta=461.33,484.03
XS Rating Curve= 0 ,0
Exp/Cntr(USF)=0,0
Exp/Cntr=0.3,0.1

Type RM Length L Ch R = 1 ,5400    ,276.6,271.2,263.6
XS GIS Cut Line= 4
2038415.45214977218356.3191211252038556.80867601218603.975755104
2038617.87469535218765.6876211282038699.29605447218887.819659803
#Sta/Elev= 30
       0 1678.84    37.5 1662.38    45.1 1657.35    52.6 1655.07    76.8 1644.55
   105.5 1635.23   134.5 1628.71     149 1621.97   156.2 1619.93   204.3 1616.51
   230.7 1616.82   254.8 1614.54   278.8 1617.38   321.6 1615.85   335.8 1612.47
   342.8 1613.14   356.9 1611.02   370.1 1612.64   374.4 1611.31   382.8 1603.57
   391.9 1601.96   402.5 1602.27   409.5 1603.63     420 1604.58   423.8 1607.58
   430.5 1615.37     434 1618.31     441  1622.5     449 1624.99   604.8 1635.68
#Mann= 3 ,-1 , 0
       0      .1       0   382.8    .045       0   409.5      .1       0
Bank Sta=382.8,409.5
XS Rating Curve= 0 ,0
Exp/Cntr(USF)=0,0
Exp/Cntr=0.3,0.1

Type RM Length L Ch R = 1 ,5129    ,95.7,92.3,88.6
XS GIS Cut Line= 4
2038223.20727408218540.6480313472038291.05840668218697.836488531
2038401.88192325218881.0345465432038500.26606552219030.307038257
#Sta/Elev= 30
       0 1754.54    21.6 1741.49    35.8 1731.42    73.3 1703.13    88.3 1690.17
   103.2 1676.23   120.6 1662.03   130.7 1655.78   156.3 1635.87   177.1 1623.11
   183.4  1618.6   201.3 1610.87   220.4 1608.83   230.4 1606.66   246.8 1599.15
  250.551598.166   258.8 1596.96   273.4 1596.53   285.6 1596.76   291.2 1598.07
   297.1 1599.48   316.5 1597.21   323.6 1597.44   345.1 1602.69   359.4 1607.73
     370 1609.27   393.2 1610.43   437.8 1610.49   481.6 1611.91   564.1 1618.82
#Mann= 3 ,-1 , 0
       0      .1       0  250.55    .045       0   291.2      .1       0
#XS Ineff= 2 , 0
                          298.28         1607.81
Permanent Ineff=
       F       F
Bank Sta=250.55,291.2
XS Rating Curve= 0 ,0
Exp/Cntr(USF)=0,0
Exp/Cntr=0.3,0.1

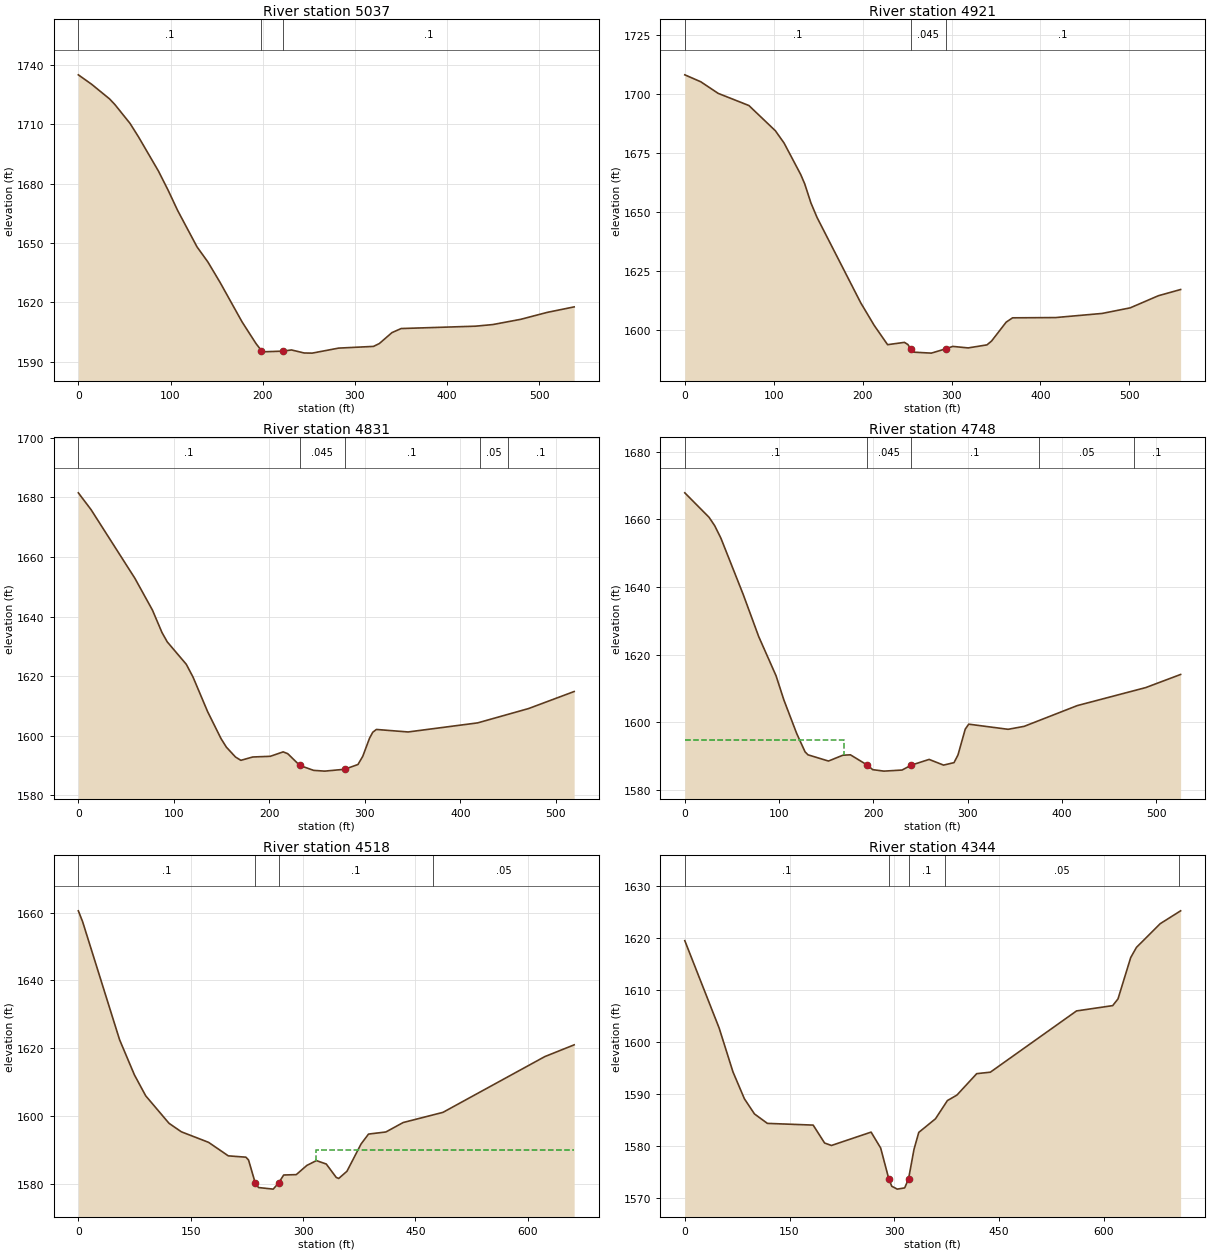
Type RM Length L Ch R = 1 ,5037    ,124.5,116.2,105.2
XS GIS Cut Line= 4
2038128.07278656218647.0876832632038204.83809765218751.092298288
2038370.75022162218941.7674258332038482.18373771219050.724641573
#Sta/Elev= 30
       0 1735.03    14.4 1730.27    33.9 1722.85    39.7 1719.99    56.1 1710.48
    65.5 1703.51    86.9 1686.41    97.3 1676.83   107.7 1666.52   128.8 1648.07
   140.5 1640.51   153.7  1630.2   177.7 1610.14   192.8 1599.21   198.6 1595.72
   201.5 1595.11   221.9 1595.42   231.2 1596.03     245 1594.49   253.7 1594.42
   282.3 1596.95   320.2 1597.82   326.5 1599.25   340.2 1604.78   350.2 1606.84
   430.8 1608.03   449.6 1608.85   479.8 1611.49   508.8 1615.02537.8688 1617.78
#Mann= 3 ,-1 , 0
       0      .1       0   198.6    .045       0   221.9      .1       0
Bank Sta=198.6,221.9
XS Rating Curve= 0 ,0
Exp/Cntr(USF)=0,0
Exp/Cntr=0.3,0.1

Type RM Length L Ch R = 1 ,4921    ,87.6,90.1,90.9
XS GIS Cut Line= 4
2038023.04643292218738.5471680892038148.57102822218879.903694333
2038335.16164286218986.2038020692038469.73305585219060.840047926
#Sta/Elev= 30
       0 1707.95    17.9 1705.02    37.6 1700.08    72.1 1694.94   101.9 1684.24
   111.7 1679.02   130.3 1665.76   134.9 1661.73   141.9 1653.61   148.8 1647.47
   197.9 1611.32     213 1601.78   228.1 1593.58     247 1594.56   250.9 1593.66
  254.13 1591.81   258.4 1590.39   277.3    1590  293.381591.811   301.4 1592.85
   318.8 1592.21   339.9  1593.5   345.2 1595.19   361.5 1603.14   368.7 1604.96
     417 1605.07   469.4 1606.82     501 1609.19   532.7 1614.33   557.7 1616.96
#Mann= 3 ,-1 , 0
       0      .1       0  254.13    .045       0  293.38      .1       0
Bank Sta=254.13,293.38
XS Rating Curve= 0 ,0
Exp/Cntr(USF)=0,0
Exp/Cntr=0.3,0.1

Type RM Length L Ch R = 1 ,4831    ,84.4,82.8,81.1
XS GIS Cut Line= 4
2038009.21036939218845.1917118822038113.21498441218951.672627264
2038266.74560659219048.2483412162038452.46813342219082.916546224
#Sta/Elev= 30
       0 1681.57    13.3 1675.93    59.3 1652.81    77.6 1642.17    87.6 1634.62
    93.1 1631.49   113.1 1623.93   120.1 1619.65   135.4 1608.03   149.4 1598.99
     155 1596.12   164.6 1592.79   170.2 1591.69   182.6 1592.81     201 1593.04
   214.5 1594.53   219.3 1593.91   231.9 1589.97   246.3 1588.32   257.9 1588.06
   278.8 1588.68   292.8 1590.29   297.8 1593.03   304.9 1599.11   308.3 1601.13
   312.1 1602.06   345.3 1601.22   418.1 1604.27   471.5 1609.09519.1561 1614.81
#Mann= 5 ,-1 , 0
       0      .1       0   231.9    .045       0   278.8      .1       0
  420.23     .05       0  450.23      .1       0
Bank Sta=231.9,278.8
XS Rating Curve= 0 ,0
Exp/Cntr(USF)=0,0
Exp/Cntr=0.3,0.1

Type RM Length L Ch R = 1 ,4748    ,244.5,229.3,205
XS GIS Cut Line= 4
2037968.76552684 218942.100565882038064.88796468219017.867663947
2038257.13284038219132.0837371532038435.80748955219110.597545164
#Sta/Elev= 30
       0 1667.82    25.7  1660.6    31.7 1658.12    38.3 1654.42      62 1637.76
    78.4 1625.34    96.8 1613.76   105.1 1606.61   118.7 1596.69   127.6 1591.26
   130.7 1590.39   152.4 1588.55   167.7 1590.27   175.7 1590.39  193.711587.337
   199.4    1586   211.3 1585.57   230.5 1585.89   240.2 1587.33   259.2 1589.03
   274.5 1587.35   285.6 1588.08   289.8 1590.34   297.5 1597.97   301.2 1599.45
     343 1597.93   360.1 1598.81   416.4 1604.94     489 1610.26     526 1614.14
#Mann= 5 ,-1 , 0
       0      .1       0  193.71    .045       0   240.2      .1       0
  376.01     .05       0  476.01      .1       0
#XS Ineff= 2 , 0
          169.34 1594.79
Permanent Ineff=
       F       F
Bank Sta=193.71,240.2
XS Rating Curve= 0 ,0
Exp/Cntr(USF)=0,0
Exp/Cntr=0.3,0.1

Type RM Length L Ch R = 1 ,4518    ,175.9,174.7,172.6
XS GIS Cut Line= 4
 2037816.1004785219237.252992678 2038020.7847285219259.870036877
2038125.95398402219236.1221404682038470.86390806 219187.49549544
#Sta/Elev= 30
       0 1660.56     5.6 1657.44    55.1  1622.5    74.9 1612.13      90 1605.95
   121.1 1597.84   137.6 1595.33   173.9 1592.22   200.3 1588.23   223.8 1587.84
   227.3    1587  236.211580.255   240.6 1578.88   260.2 1578.41  267.531580.254
   274.2 1582.58     291 1582.69   305.1  1585.4   317.9 1586.83   331.1 1585.82
   344.4 1581.86   347.7 1581.56   358.7 1583.68   377.5 1591.72   387.5 1594.66
   410.7 1595.28   433.8 1598.07   486.9 1601.07   622.9 1617.53   662.1    1621
#Mann= 4 ,-1 , 0
       0      .1       0  236.21    .045       0  267.53      .1       0
  473.75     .05       0
#XS Ineff= 2 , 0
                        316.9253         1589.93
Permanent Ineff=
       F       T
Bank Sta=236.21,267.53
XS Rating Curve= 0 ,0
Exp/Cntr(USF)=0,0
Exp/Cntr=0.3,0.1

Type RM Length L Ch R = 1 ,4344    ,188.3,206.7,232.4
XS GIS Cut Line= 4
2037814.96962629 219428.367016162038058.10285143   219432.890425
 2038225.4689785219384.2637799722038485.56498679219249.692366988
#Sta/Elev= 30
       0 1619.47    49.3 1602.62      69 1594.22    85.4 1589.04    99.8 1586.13
   118.3 1584.31   183.9 1583.98   200.3 1580.53   210.1 1580.06   266.9 1582.63
   280.6 1579.57  292.24 1573.64   296.5 1572.21   304.4 1571.66     315  1571.9
  320.571573.643   328.3 1579.29   335.2 1582.58   359.1 1585.19   376.2  1588.7
   389.8 1589.75   418.2 1593.88   437.7 1594.16   561.2 1605.95     613 1606.97
   620.6 1608.27   638.8 1616.22     647 1618.17   681.1 1622.74   710.3 1625.21
#Mann= 5 ,-1 , 0
       0      .1       0  292.24    .045       0  320.57      .1       0
  373.18     .05       0  707.46      .1       0
Bank Sta=292.24,320.57
XS Rating Curve= 0 ,0
Exp/Cntr(USF)=0,0
Exp/Cntr=0.3,0.1

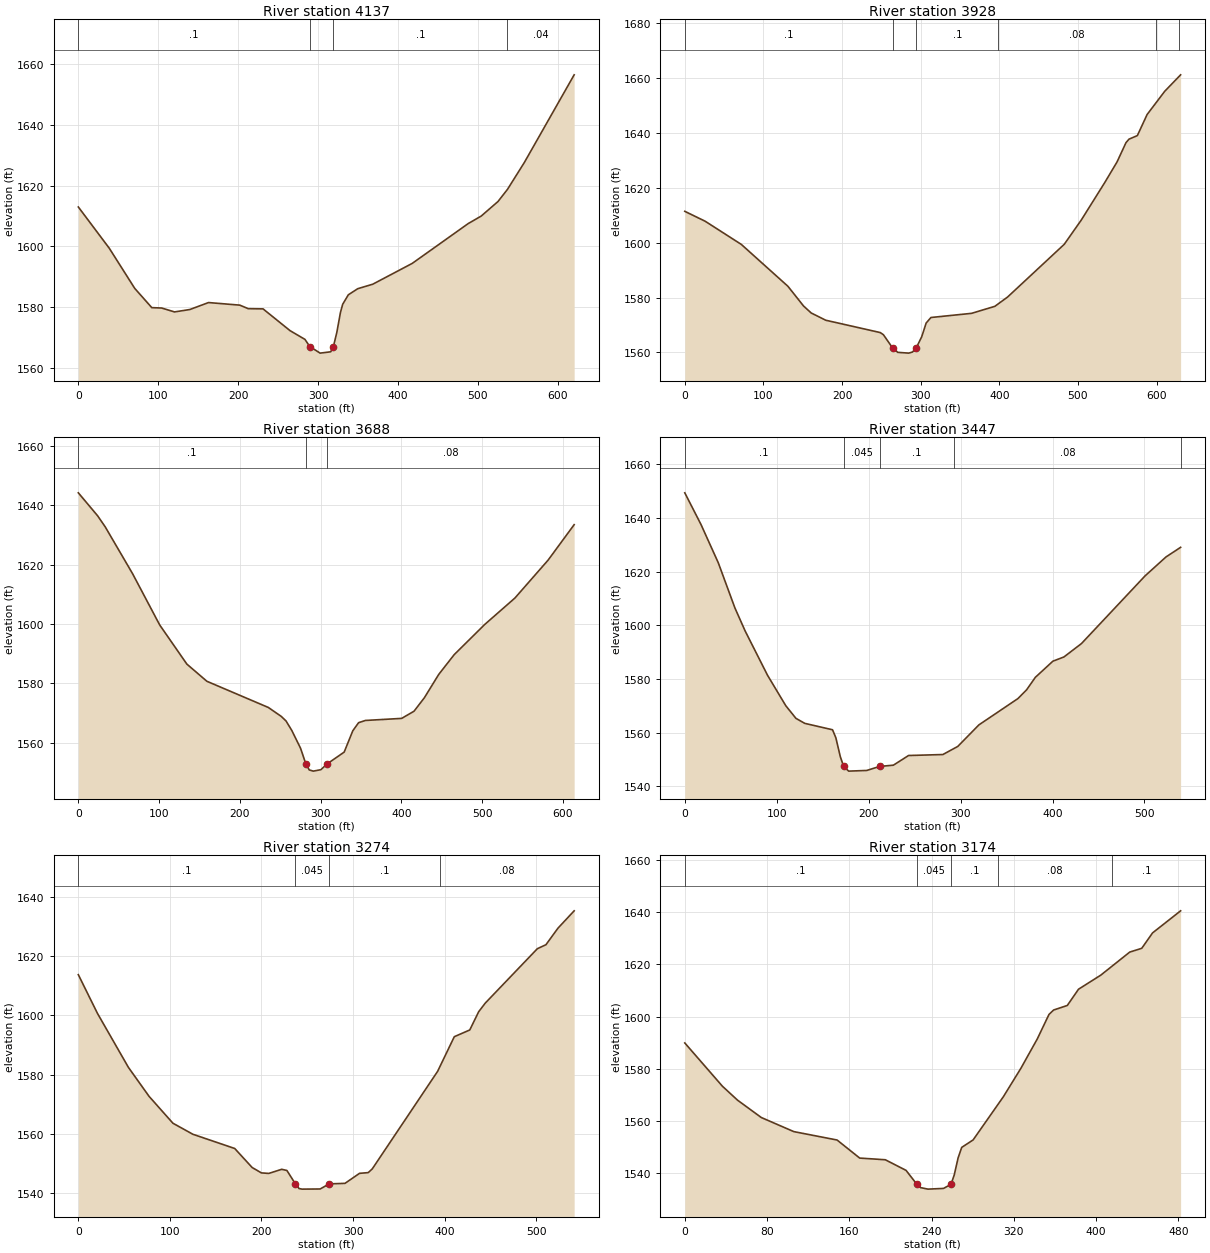
Type RM Length L Ch R = 1 ,4137    ,208.5,209.2,208.5
XS GIS Cut Line= 4
 2037828.5398528219482.6479222382038036.61665944219568.592690195
2038167.79551579219662.4534236212038353.25527822219804.940802075
#Sta/Elev= 30
       0 1612.99    38.7 1599.43    70.6 1586.21    91.9 1579.89   104.3 1579.76
   120.3 1578.48   139.5 1579.27   162.9 1581.56     202 1580.71   212.6 1579.55
   231.1 1579.48   264.9 1572.32   283.5 1569.45  289.541567.099   302.5 1564.93
   315.8 1565.37  319.111567.099   323.4 1571.76   327.9 1578.27   330.7 1580.98
   337.8 1584.12   349.6 1586.12   368.4  1587.6   417.8 1594.45   487.8 1607.54
     504    1610     525 1614.78   536.9 1618.79     558 1627.63   620.3 1656.45
#Mann= 4 ,-1 , 0
       0      .1       0  289.54    .045       0  319.11      .1       0
  536.43     .04       0
Bank Sta=289.54,319.11
XS Rating Curve= 0 ,0
Exp/Cntr(USF)=0,0
Exp/Cntr=0.3,0.1

Type RM Length L Ch R = 1 ,3928    ,243.6,239.5,233.1
XS GIS Cut Line= 4
2037741.46423264219646.6214926812037934.83996054219747.267339367
2038072.80393015219847.913186053  2038282.011589219968.914372518
#Sta/Elev= 30
       0 1611.46    25.9 1607.85    71.9 1599.39   131.1 1584.14     151 1576.94
   160.7  1574.4   179.2 1571.75   248.5 1567.25   252.5 1566.48  264.171561.674
   270.9 1560.03   284.7 1559.75   289.6 1560.16  294.361561.676   301.3 1565.75
   306.9 1570.71     313 1572.74   364.7 1574.26   394.3 1576.82   410.4 1580.19
   482.5 1599.43   504.2 1608.29     534 1621.94   549.7  1629.5     561 1636.49
   564.8 1637.77   575.5 1639.09   587.9 1646.77   610.3 1655.24   630.5 1661.24
#Mann= 6 ,-1 , 0
       0      .1       0  264.17    .045       0  294.36      .1       0
  398.77     .08       0  598.77     .04       0  628.77     .06       0
Bank Sta=264.17,294.36
XS Rating Curve= 0 ,0
Exp/Cntr(USF)=0,0
Exp/Cntr=0.3,0.1

Type RM Length L Ch R = 1 ,3688    ,238.9,241.6,246.1
XS GIS Cut Line= 4
2037621.59389838219859.2217081532037835.32496606219975.699485778
2037971.02723126220036.7655051152038179.10403789220113.663455392
#Sta/Elev= 30
       0 1644.26    23.8 1636.55    33.3 1632.79    67.2 1616.99   100.8  1599.7
   134.4 1586.52   159.2 1580.73   235.3  1571.9   251.3 1568.89   257.2 1567.35
   264.4 1564.12   275.2 1558.15  281.731552.891     286 1550.84     291 1550.44
   300.4 1550.93  308.151552.889   329.2 1556.85   339.9 1564.05   347.1 1566.78
   355.5 1567.52   400.4 1568.22   415.7 1570.64   428.5 1575.17   446.3 1583.04
   465.4 1589.69   503.3 1599.89   540.6 1608.78   581.7 1621.56     614 1633.52
#Mann= 3 ,-1 , 0
       0      .1       0  281.73    .045       0  308.15     .08       0
Bank Sta=281.73,308.15
XS Rating Curve= 0 ,0
Exp/Cntr(USF)=0,0
Exp/Cntr=0.3,0.1

Type RM Length L Ch R = 1 ,3447    ,194.2,172.4,149.6
XS GIS Cut Line= 4
 2037543.5650959220058.2516971042037662.30457794220119.317716442
2037788.96002546220216.5710064982037999.29853651220344.357306223
#Sta/Elev= 30
       0 1649.42    17.6 1637.63    36.4 1623.38    54.5 1606.54    65.7  1597.9
      90 1581.44   109.8 1570.12   120.9 1565.38   130.5 1563.52   160.7 1561.13
   164.3 1558.17   169.1 1551.19  172.761547.466   178.3 1545.72   197.9 1545.97
  211.881547.469   226.9 1547.94   243.4 1551.54   280.7  1551.9   296.9 1554.91
   319.9 1562.95   362.3 1572.74   371.8 1576.02   381.3 1580.67   400.4 1586.69
   412.4 1588.26   431.5 1593.26   500.7 1618.49   523.4 1625.52   539.3 1629.11
#Mann= 5 ,-1 , 0
       0      .1       0  172.76    .045       0  211.88      .1       0
  293.21     .08       0  539.32     .04       0
Bank Sta=172.76,211.88
XS Rating Curve= 0 ,0
Exp/Cntr(USF)=0,0
Exp/Cntr=0.3,0.1

Type RM Length L Ch R = 1 ,3274    ,84.1,100.6,116
XS GIS Cut Line= 4
2037429.32169809220222.105895245 2037607.7005836220321.025095393
2037717.97116738220308.0520855382037915.80956767 220418.32266931
#Sta/Elev= 30
       0 1613.67    20.9 1600.63    54.7 1582.45    77.2 1572.71   103.3 1563.64
   125.1 1559.92   170.8 1555.13   189.8 1548.73   199.9 1546.91     208 1546.73
   222.1 1548.12   227.8 1547.72   236.8 1543.33     241 1541.64   244.3 1541.44
   264.1 1541.49     274 1543.21   291.2 1543.38   307.1 1546.76   316.6    1547
     321 1548.25   392.4 1581.12   410.6 1592.78   427.5 1595.05   437.2 1601.18
   444.4 1604.09   501.3 1622.42   510.7 1623.77   523.8 1629.33   541.5 1635.18
#Mann= 4 ,-1 , 0
       0      .1       0   236.8    .045       0     274      .1       0
     395     .08       0
Bank Sta=236.8,274
XS Rating Curve= 0 ,0
Exp/Cntr(USF)=0,0
Exp/Cntr=0.3,0.1

Type RM Length L Ch R = 1 ,3174    ,148.2,143.7,137.8
XS GIS Cut Line= 4
2037427.44224526220287.5972543462037540.43362596220360.371363947
2037737.68976514220459.9569876112037852.59625399220513.580015738
#Sta/Elev= 30
       0 1589.95    36.6 1573.39    51.3 1568.06    74.4 1561.42     106 1556.03
   148.1 1552.81   170.1  1545.9     195 1545.26   215.2 1541.19   225.71535.861
   229.2 1534.61   236.5 1534.02   251.6 1534.29  258.911535.861     262 1539.39
   265.8 1545.96   269.3 1549.98   280.4 1552.85   309.8 1569.37   326.9 1580.28
   342.8 1591.49   354.2 1600.87   358.7 1602.56     372  1604.3   382.9 1610.51
   404.6 1615.91   432.7 1624.72   444.4 1626.17   454.9 1632.06   482.2 1640.51
#Mann= 5 ,-1 , 0
       0      .1       0   225.7    .045       0  258.91      .1       0
   304.4     .08       0  415.37      .1       0
Bank Sta=225.7,258.91
XS Rating Curve= 0 ,0
Exp/Cntr(USF)=0,0
Exp/Cntr=0.3,0.1

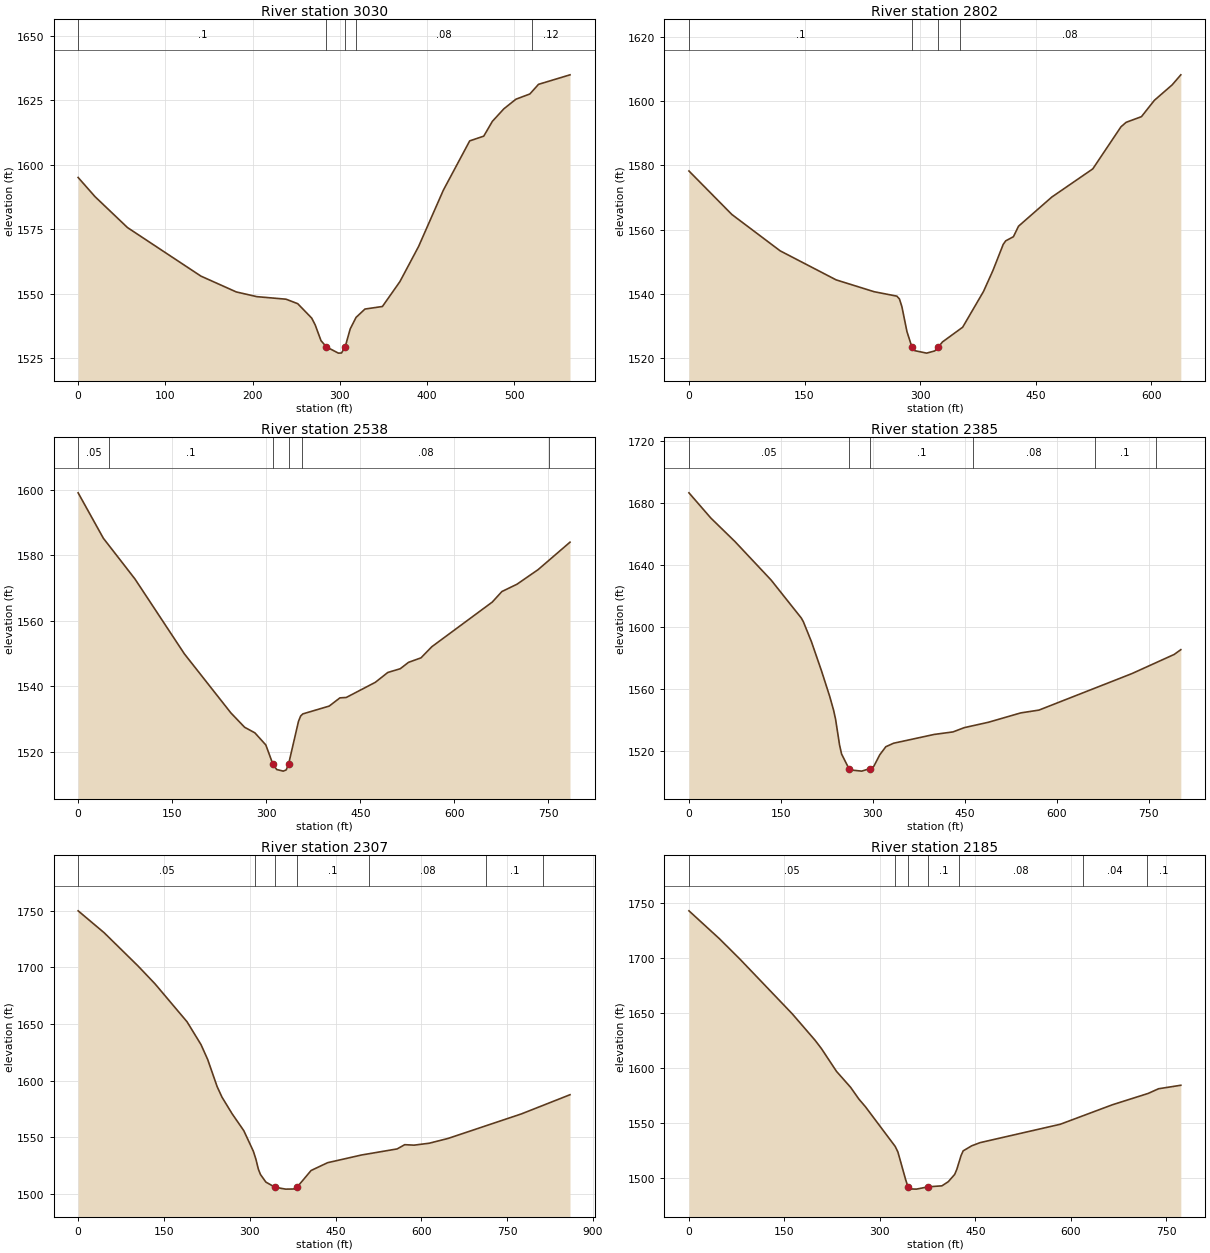
Type RM Length L Ch R = 1 ,3030    ,234.1,228.4,222.3
XS GIS Cut Line= 4
 2037287.6393505220465.7023120532037481.06527339220511.664907591
2037668.74587184220549.967070539 2037841.1056051 220571.03326016
#Sta/Elev= 30
       0 1595.14    19.4 1587.69    56.6 1575.71   140.8 1556.89   181.3 1550.76
   204.9 1548.93   238.4 1547.94   251.8  1546.2   267.8 1540.62   271.8    1538
   278.5 1531.86  284.741529.435   298.4 1527.03     302 1527.08  306.17 1529.44
     312 1536.44   318.7 1540.89   328.9 1544.12   348.9 1545.11     369 1554.78
   390.4 1568.39   418.8 1590.23     449 1609.33   465.1 1611.16     475 1616.91
   488.2 1621.77     502 1625.49     518 1627.52   527.9 1631.25     564 1634.94
#Mann= 5 ,-1 , 0
       0      .1       0  284.74    .045       0  306.17      .1       0
  318.81     .08       0  520.36     .12       0
Bank Sta=284.74,306.17
XS Rating Curve= 0 ,0
Exp/Cntr(USF)=0,0
Exp/Cntr=0.3,0.1

Type RM Length L Ch R = 1 ,2802    ,254.6,264,271.6
XS GIS Cut Line= 4
 2037251.2522957 220739.562777132037431.27246156220760.628966752
2037653.42500666220751.0534260152037885.15309249220712.751263067
#Sta/Elev= 30
       0 1578.29    55.7 1564.74   118.4 1553.41   191.1 1544.36   240.3 1540.68
   269.9 1539.29   273.2 1538.43   276.4 1536.05     283 1528.24  289.391523.461
   292.9 1522.32   308.5 1521.54   319.1 1522.23  323.741523.459   329.1 1525.03
   355.3 1529.61   382.4 1540.77   394.7 1547.34   407.9  1555.4   411.2 1556.53
   421.2 1557.81   427.8 1561.08     471 1570.16   524.2 1578.94   560.8 1592.05
   567.5 1593.45   587.4 1595.22   604.1 1600.29   627.3 1605.13   638.5 1608.25
#Mann= 4 ,-1 , 0
       0      .1       0  289.39    .045       0  323.74      .1       0
  351.25     .08       0
Bank Sta=289.39,323.74
XS Rating Curve= 0 ,0
Exp/Cntr(USF)=0,0
Exp/Cntr=0.3,0.1

Type RM Length L Ch R = 1 ,2538    ,159,152.7,133.5
XS GIS Cut Line= 4
2037253.16740385220952.1397814912037486.81059783220988.526836291
2037661.08543925221049.8102970082038021.12577096221097.688000693
#Sta/Elev= 30
       0 1599.12    40.2 1585.24    90.6 1572.79   169.5 1549.87   243.6 1531.83
   265.5 1527.44   281.9 1525.73   299.3 1522.04  310.721516.099   316.7 1514.52
   327.1 1514.03   331.8  1514.4  335.531516.101   351.4 1529.24   354.9  1530.9
   358.4 1531.53   400.4 1533.92   417.5 1536.43   427.6 1536.55     474 1541.19
   493.8 1544.19   513.7 1545.34   526.9 1547.29   546.8 1548.67     564 1552.06
   660.4 1565.71   675.8 1568.94   699.8 1571.17   733.5 1575.63   784.4 1584.03
#Mann= 6 ,-1 , 0
       0     .05       0      50      .1       0  310.72    .045       0
  335.53      .1       0  356.46     .08       0   751.2     .04       0
Bank Sta=310.72,335.53
XS Rating Curve= 0 ,0
Exp/Cntr(USF)=0,0
Exp/Cntr=0.3,0.1

Type RM Length L Ch R = 1 ,2385    ,91.4,78.4,50.1
XS GIS Cut Line= 4
2037231.48329779221152.9193523792037385.53778983221148.054473683
2037713.10628868221135.0814638282038032.56665637221164.270736003
#Sta/Elev= 30
       0 1686.86    35.7  1670.6    75.1 1655.42   134.2 1630.54   183.4 1606.06
   186.7 1603.71   199.9 1590.82   216.3 1572.03   229.7 1555.55     236 1546.69
   239.3 1540.77   245.8 1524.16   249.1 1518.33  261.09 1508.95   265.5 1508.01
   281.9 1507.33   295.1 1508.94   301.6 1510.39   311.5 1517.93   321.3 1523.08
   333.9 1525.32   400.2    1531   430.9 1532.63   449.4 1535.39   488.8 1538.86
   541.5 1544.89   571.2  1546.7   722.7 1570.21   791.9 1582.61   802.7 1585.68
#Mann= 6 ,-1 , 0
       0     .05       0  261.09    .045       0   295.1      .1       0
  464.13     .08       0  661.96      .1       0  761.96     .04       0
Bank Sta=261.09,295.1
XS Rating Curve= 0 ,0
Exp/Cntr(USF)=0,0
Exp/Cntr=0.3,0.1

Type RM Length L Ch R = 1 ,2307    ,108.3,121.6,134.9
XS GIS Cut Line= 5
2037215.26703547221264.8115623832037503.91650476221242.108795136
2037600.99031371221156.8664911682037705.03310037221151.628244365
2038040.67478753221179.615288276
#Sta/Elev= 30
       01749.901  45.5031730.561 104.4861701.344 134.3591685.491 190.3861651.976
 214.7941631.832 226.5061618.637 242.9611594.778 251.4061585.511 269.289 1570.71
 289.5411555.912 306.3341537.667   310.71530.741 315.0661521.886 318.6031517.288
 328.1651510.513 344.1751505.943 362.7731504.309 376.1931504.412 382.297 1505.81
 407.1581520.745 436.001 1527.63 495.1311534.406 557.6221539.794 570.7911543.525
 587.2521543.114  613.591544.813 646.5121549.018 774.9091570.716  859.711587.615
#Mann= 7 ,-1 , 0
       0     .05       0  309.54      .1       0 344.175    .045       0
 382.297      .1       0  508.73     .08       0   712.9      .1       0
   812.9     .04       0
Bank Sta=344.175,382.297
XS Rating Curve= 0 ,0
Exp/Cntr(USF)=0,0
Exp/Cntr=0.3,0.1

Type RM Length L Ch R = 1 ,2185    ,218.8,226.6,236
XS GIS Cut Line= 4
2037272.31848533221306.4347887582037536.60340967221298.774356169
2037777.90703624221252.8117606312038040.27685243221233.660679157
#Sta/Elev= 30
       0    1743    47.9  1717.6    80.2 1698.99   162.3 1649.28   198.4 1625.06
   208.2 1617.61   231.9 1596.87   254.2 1582.25   267.3 1571.48   277.4 1564.65
   324.1 1528.59   328.4 1523.51   340.8 1497.87  344.32 1491.78   347.5 1489.84
   357.5 1489.66  376.211491.783   397.6 1492.65   407.6 1496.43   417.6    1503
     421 1507.62   427.7 1520.22     431 1524.49   444.4 1529.09   457.7    1532
   583.5 1548.68   665.7 1566.49   721.7 1576.76   738.1 1581.03   773.1 1584.21
#Mann= 7 ,-1 , 0
       0     .05       0   324.4      .1       0  344.32    .045       0
  376.21      .1       0   424.4     .08       0  620.04     .04       0
  720.04      .1       0
Bank Sta=344.32,376.21
XS Rating Curve= 0 ,0
Exp/Cntr(USF)=0,0
Exp/Cntr=0.3,0.1