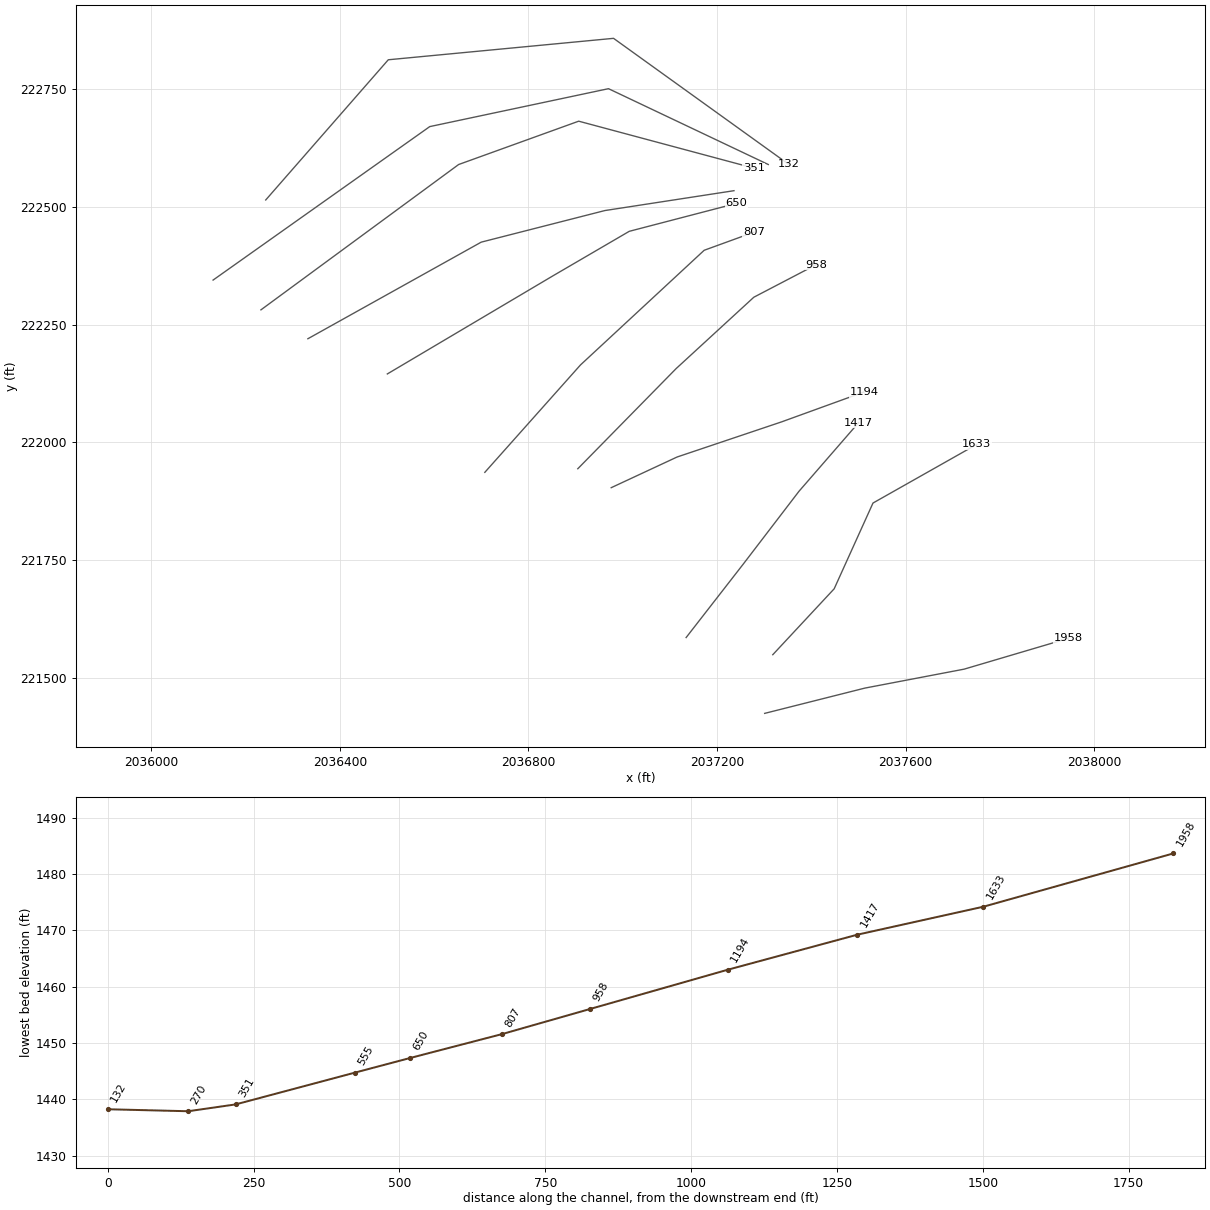
HEC-RAS study LTLSTNYCK.prj: LTLSTNYCK

--- LTLSTNYCK.g01 (geometry) --- (continued)

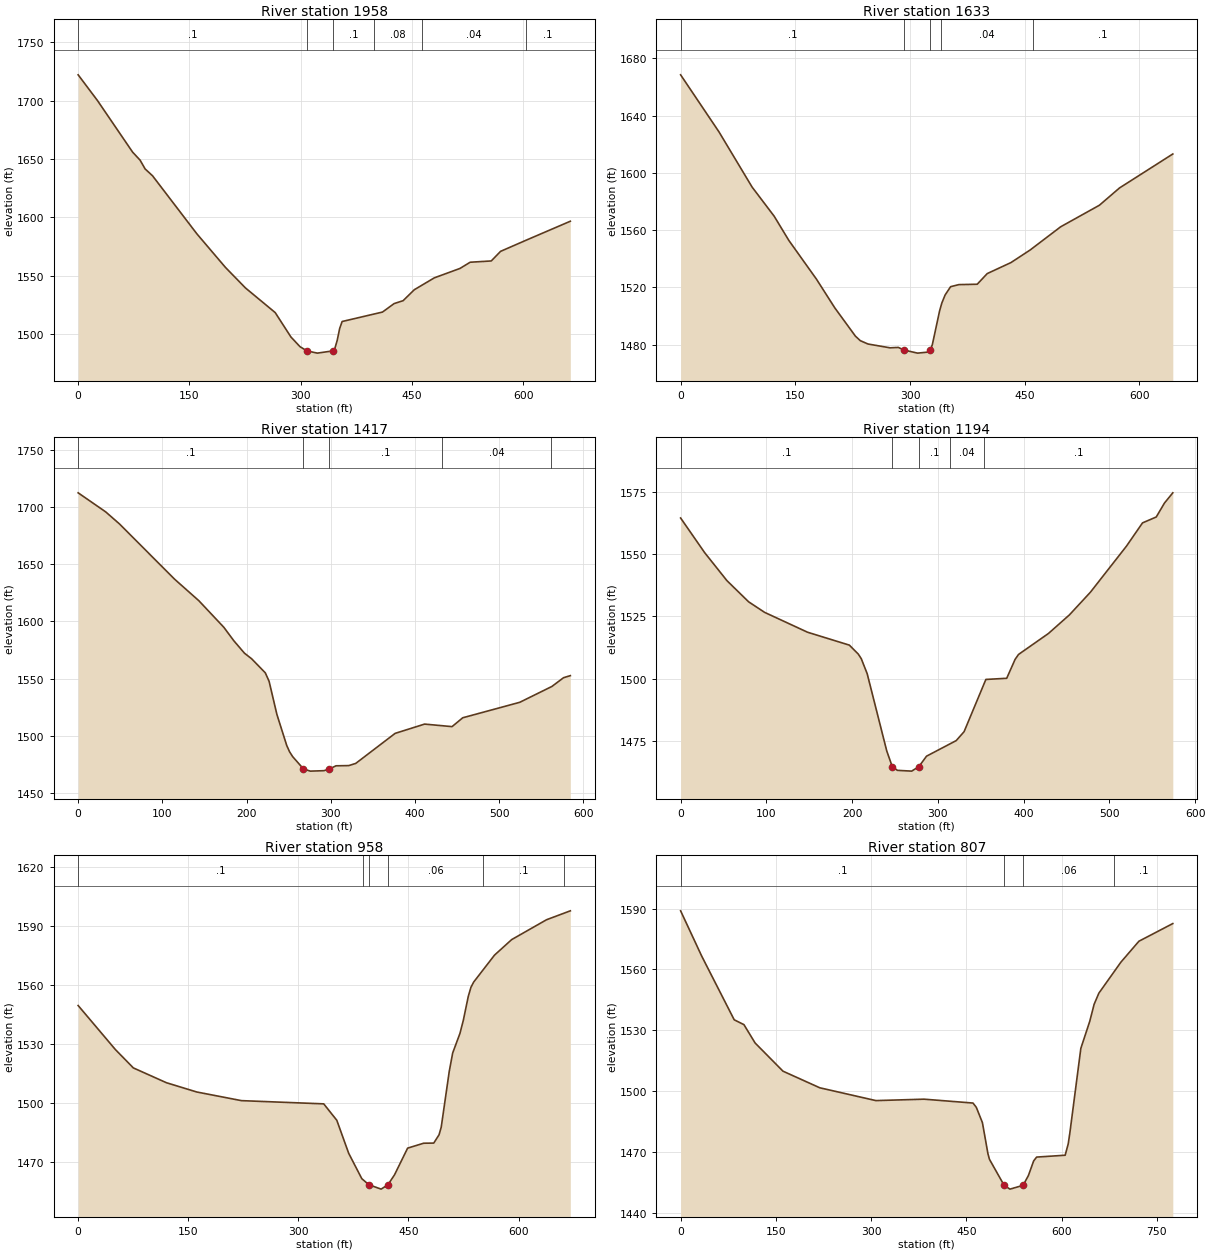
Type RM Length L Ch R = 1 ,1958    ,301.6,325.7,348.5
XS GIS Cut Line= 4
2037301.04510754221425.171493897 2037513.6221119221478.794522024
2037724.28400811221519.0117931192037944.52144506 221584.12547013
#Sta/Elev= 30
       0 1722.05      26 1700.06    73.4 1655.84    83.5 1648.94    90.3 1641.41
   100.2 1635.62     160 1585.86   198.6 1557.03   225.5 1539.49   265.6 1518.37
   286.8 1497.47     299 1489.18  308.331485.568   322.4 1483.64  343.411485.565
   345.8 1487.23   349.1 1494.37   352.5 1504.75   355.8 1510.72   410.2 1518.82
   425.9 1526.09     438 1528.56   453.1 1537.96   480.2 1548.17   514.6 1556.17
   528.4 1561.51   556.8  1562.6   569.4 1570.83   603.7 1580.34   663.4 1596.63
#Mann= 6 ,-1 , 0
       0      .1       0  308.33    .045       0  343.41      .1       0
  399.24     .08       0   463.7     .04       0   603.7      .1       0
Bank Sta=308.33,343.41
XS Rating Curve= 0 ,0
Exp/Cntr(USF)=0,0
Exp/Cntr=0.3,0.1

Type RM Length L Ch R = 1 ,1633    ,204.4,215.9,202.9
XS GIS Cut Line= 4
2037318.28108086221549.6535234772037448.50843489221689.456418237
2037530.85808522221871.3916922392037751.09552217221995.873721819
#Sta/Elev= 30
       0 1668.43    50.2 1628.59    93.5 1590.08   122.4 1569.72   141.6  1552.8
   177.6 1525.86   201.8 1505.65   228.7 1485.98     235 1482.88   245.1 1480.54
   273.9 1477.88   284.7 1478.17  292.261476.315   309.9 1474.18   324.2 1474.94
  326.441476.319   329.2 1480.04   338.7 1503.64   341.6  1509.1   345.9 1514.75
   353.1 1520.55   363.9    1522   387.9 1522.26     401  1529.7   432.1  1537.4
   457.2 1546.19   497.1 1562.38   547.7  1577.4     574 1589.47   643.7 1613.17
#Mann= 5 ,-1 , 0
       0      .1       0  292.26    .045       0  326.44      .1       0
  341.06     .04       0  460.76      .1       0
Bank Sta=292.26,326.44
XS Rating Curve= 0 ,0
Exp/Cntr(USF)=0,0
Exp/Cntr=0.3,0.1

Type RM Length L Ch R = 1 ,1417    ,234.1,222.4,203.9
XS GIS Cut Line= 4
2037134.43069871221586.040578278  2037255.082512221741.164338216
2037373.81921714221896.2880981552037500.21635487222041.836317357
#Sta/Elev= 30
       0 1712.32    32.7 1695.69    49.1 1685.14   114.5 1636.92   143.5 1617.98
     173 1594.89     185 1583.02   197.5 1572.28   206.1 1567.32   222.3 1555.08
   226.8 1547.67   236.1 1518.65   247.8 1491.53   251.2 1486.02   254.8 1481.88
  267.63 1471.13   275.8 1469.22     292  1469.6  298.29 1471.13   306.3 1473.87
   321.4 1474.05   329.7 1475.95   376.5  1502.2   411.5  1510.3   444.1 1508.09
   456.8 1515.82   524.5 1529.33   562.7 1543.18   576.6 1550.86   584.6 1552.62
#Mann= 5 ,-1 , 0
       0      .1       0  267.63    .045       0  298.29      .1       0
  431.87     .04       0  561.87      .1       0
Bank Sta=267.63,298.29
XS Rating Curve= 0 ,0
Exp/Cntr(USF)=0,0
Exp/Cntr=0.3,0.1

Type RM Length L Ch R = 1 ,1194    ,225,236.1,242.7
XS GIS Cut Line= 4
2036975.47672248221903.9485307452037115.27961724221969.062207756
2037337.43216234222043.7514255042037511.70700375222106.949994368
#Sta/Elev= 30
       0 1564.42    28.1 1550.51      54 1539.33    79.3 1530.84      98  1526.6
   148.1 1518.64   196.8 1513.48   207.2 1509.89   210.7 1508.04   217.6 1502.01
   240.4 1471.08  246.811464.806   252.8  1463.3   269.5 1462.99  277.871464.805
   286.8 1468.98   321.4 1475.22   330.6  1478.8     356 1499.73   380.3 1500.19
   390.1 1507.78   394.1 1509.75     429 1518.15   453.5 1525.62   477.9 1534.68
   519.8 1553.07   538.7 1562.47   554.7 1564.83   564.3 1570.42     574 1574.51
#Mann= 5 ,-1 , 0
       0      .1       0  246.81    .045       0  277.87      .1       0
  314.22     .04       0  354.22      .1       0
Bank Sta=246.81,277.87
XS Rating Curve= 0 ,0
Exp/Cntr(USF)=0,0
Exp/Cntr=0.3,0.1

Type RM Length L Ch R = 1 ,958     ,150.5,151,149.4
XS GIS Cut Line= 4
2036904.61772103 221944.165801842037113.36450909  222156.7428062
2037278.06380977222308.0363498442037410.20627194 222376.98024315
#Sta/Elev= 30
       0 1549.41    50.7 1527.03    75.2 1517.68   120.3 1510.14   161.6 1505.43
   222.5 1501.03   334.6 1499.39   352.4 1491.05   368.6 1474.26   386.5 1461.32
  396.141458.258   412.8 1456.02  422.121458.258   431.1 1463.33   448.9 1476.87
   470.8 1479.37   484.5 1479.44   491.7 1483.64   494.7 1487.55   505.6 1515.88
   510.3 1525.27   520.2 1535.23   524.8  1541.9   531.6 1554.14   535.2 1558.69
   538.9 1561.35   567.3 1575.05   590.7 1582.95   638.2 1593.05   670.6 1597.58
#Mann= 6 ,-1 , 0
       0      .1       0  387.93     .04       0  396.14    .045       0
  422.12     .06       0  551.57      .1       0  661.57     .06       0
Bank Sta=396.14,422.12
XS Rating Curve= 0 ,0
Exp/Cntr(USF)=0,0
Exp/Cntr=0.3,0.1

Type RM Length L Ch R = 1 ,807     ,161.3,157.5,150.9
XS GIS Cut Line= 4
2036707.36158184 221936.505369252036910.36304547 222164.40323879
2037172.73286166222407.6219735092037278.06380977222445.924136457
#Sta/Elev= 30
       0 1588.94    33.3 1566.53    84.4 1535.14    99.7 1532.76   117.3  1523.7
   161.2 1509.78   219.2 1501.58   307.5 1495.26   383.5 1495.96   460.4 1494.05
   465.6 1491.94   475.2 1484.41   483.9 1469.08   486.3 1466.29   509.41453.428
   518.6 1451.56  539.211453.428   547.6 1458.24   555.9 1465.48   560.6 1467.38
   605.5 1468.29   610.3 1473.87   612.8 1479.06   630.2 1521.04   644.3 1534.47
   651.1  1542.8   658.6 1548.31   693.4 1563.65   721.6 1573.92     775 1582.65
#Mann= 4 ,-1 , 0
       0      .1       0   509.4    .045       0  539.21     .06       0
  682.96      .1       0
Bank Sta=509.4,539.21
XS Rating Curve= 0 ,0
Exp/Cntr(USF)=0,0
Exp/Cntr=0.5,0.3

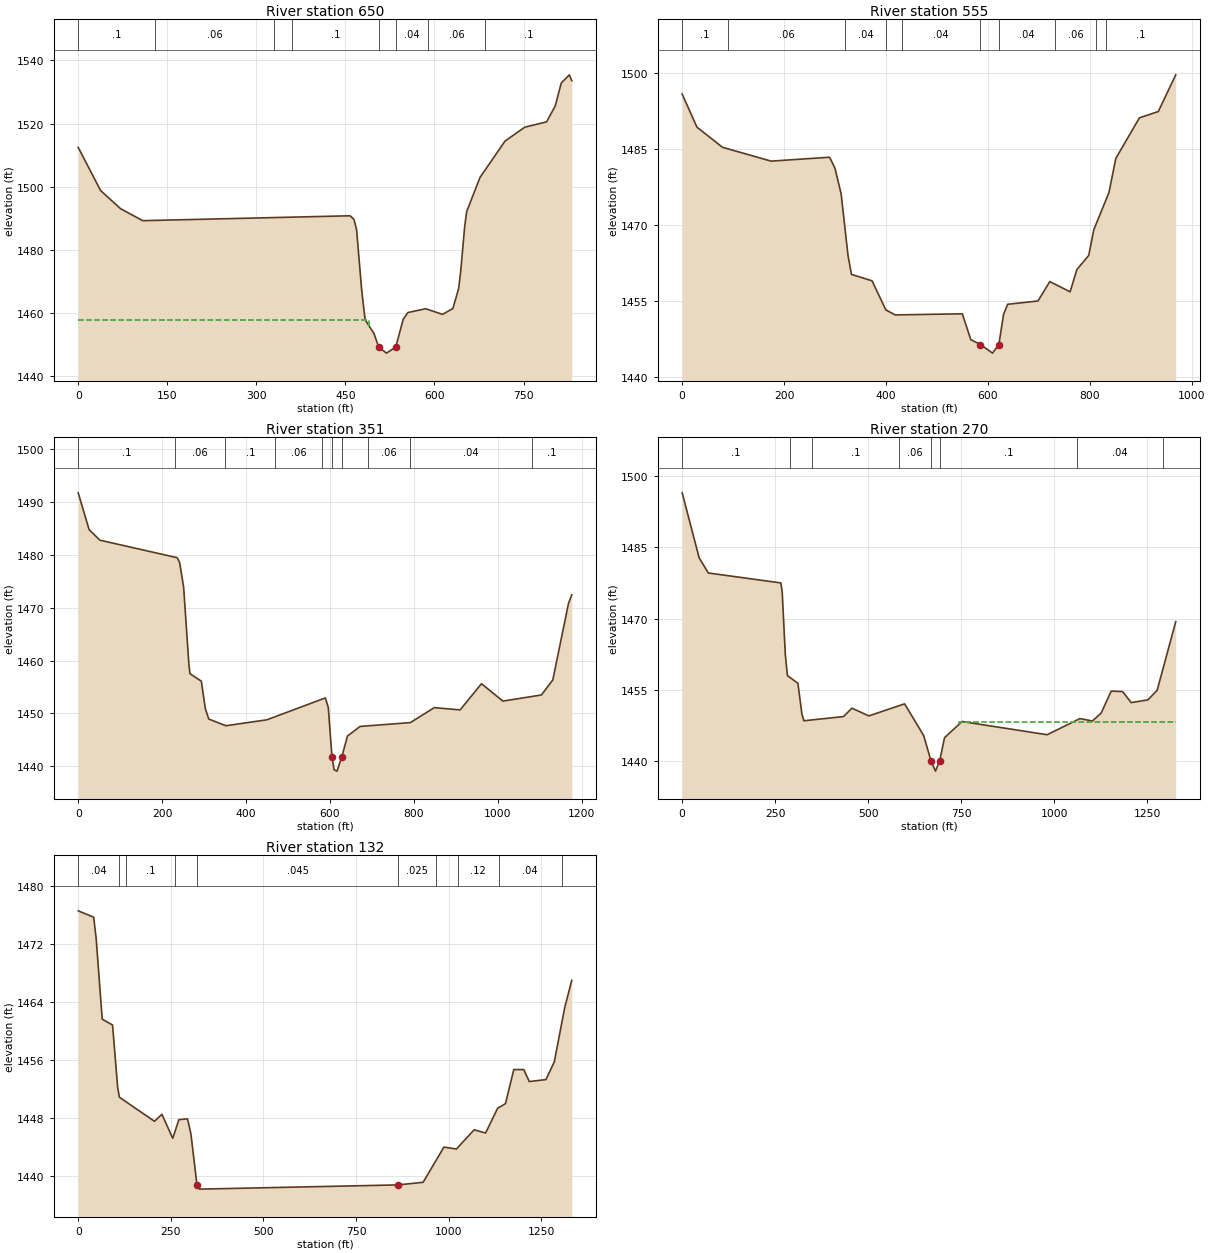
Type RM Length L Ch R = 1 ,650     ,103.2,94.4,84.7
XS GIS Cut Line= 4
2036500.52990193222145.2521573162036852.90980105222353.998945382
2037013.77888543222447.8392446042037241.67675497222507.207597173
#Sta/Elev= 30
       0 1512.44    37.7 1498.79    71.2 1493.06   108.6 1489.25     458  1490.8
   464.5 1489.63   468.9 1486.36   477.5 1467.14   483.2 1457.88     498 1453.58
  506.231449.217   519.2 1447.32  534.821449.213   547.3 1457.97   555.2 1460.16
   585.3 1461.38   613.6 1459.59     631 1461.43   640.7  1467.7   644.1 1472.96
   650.9 1487.34   654.3 1492.12   676.7 1502.91   718.7 1514.41     752 1518.83
   788.9 1520.54   803.4 1525.54   813.6 1532.82   827.2 1535.42   831.3 1533.57
#Mann= 8 ,-1 , 0
       0      .1       0     130     .06       0     330     .04       0
     360      .1       0  506.23    .045       0  534.82     .04       0
  589.57     .06       0  685.81      .1       0
#XS Ineff= 2 , 0
             490 1457.75
Permanent Ineff=
       F       F
Bank Sta=506.23,534.82
XS Rating Curve= 0 ,0
Exp/Cntr(USF)=0,0
Exp/Cntr=0.5,0.3

Type RM Length L Ch R = 1 ,555     ,199.4,204.4,211.1
XS GIS Cut Line= 4
2036332.00038496222219.9413750642036699.70114926222424.857946835
2036962.07096545222491.8867319942037235.93143053222534.019111237
#Sta/Elev= 30
       0 1495.84      29 1489.32    79.1 1485.35   174.5 1482.62   289.4 1483.39
   299.9 1481.22     312 1476.17   325.5 1464.01   332.3 1460.26   372.7    1459
   399.7 1453.26   418.1 1452.27   549.9 1452.49   566.5  1447.4  585.541446.427
   609.2 1444.73  621.611446.424   630.8 1452.37   638.9 1454.37   698.4 1455.02
   721.6 1458.85   761.5 1456.83   774.7 1461.22     798    1464   807.9 1469.06
   837.8 1476.44   851.1 1483.14   897.5 1491.16   934.6 1492.41   968.8 1499.65
#Mann= 10 ,-1 , 0
       0      .1       0      90     .06       0     320     .04       0
     400      .1       0  430.94     .04       0  585.54    .045       0
  621.61     .04       0  731.74     .06       0  811.74     .04       0
  831.74      .1       0
Bank Sta=585.54,621.61
XS Rating Curve= 0 ,0
Exp/Cntr(USF)=0,0
Exp/Cntr=0.5,0.3

Type RM Length L Ch R = 1 ,351     ,84.8,81.2,89.1
XS GIS Cut Line= 4
2036232.41476129222281.2248357812036651.82344557222589.557247511
2036906.53282917222681.4824385862037278.06380977222581.896814921
#Sta/Elev= 30
       0 1491.75    25.9 1484.79    51.7 1482.79   236.1 1479.47   241.9 1478.47
   251.2 1473.88   263.8 1459.18   266.3 1457.52   293.4 1456.11   302.8 1450.94
   311.1 1448.94   351.8 1447.68   449.6  1448.8   588.8 1452.94   595.8 1451.16
  604.621441.794   609.7 1439.34   616.7 1439.09   628.11441.794   641.5 1445.73
   671.7 1447.55   791.3 1448.27   848.4  1451.1     910 1450.68   960.9 1455.63
  1011.8 1452.34  1103.6  1453.5  1130.8 1456.34  1168.1  1470.81175.986 1472.46
#Mann= 10 ,-1 , 0
       0      .1       0     230     .06       0     350      .1       0
     470     .06       0  580.55      .1       0  604.62    .045       0
   628.1      .1       0  690.55     .06       0  790.55     .04       0
 1081.34      .1       0
Bank Sta=604.62,628.1
XS Rating Curve= 0 ,0
Exp/Cntr(USF)=0,0
Exp/Cntr=0.3,0.1

Type RM Length L Ch R = 1 ,270     ,257,138.1,298.2
XS GIS Cut Line= 4
2036130.91402948222344.4234046452036590.53998485222669.991789701
2036969.73139804222750.4263318922037308.70554013222589.557247511
#Sta/Elev= 30
       0 1496.45    45.6 1482.77    70.2 1479.58   265.2 1477.49   268.8 1475.54
     277 1462.48   282.8 1457.97   310.9 1456.38   321.7  1449.9     327 1448.48
   433.4 1449.36   456.1 1451.13   501.5  1449.5   597.6 1452.04   648.9 1445.36
  668.63 1440.01   680.5 1437.88  691.711440.007   704.9 1444.92   751.9 1448.32
   980.6 1445.54  1068.7 1448.94  1102.2 1448.43  1125.6 1450.09  1152.8 1454.72
  1183.4 1454.62  1206.4  1452.3  1251.1 1452.87  1276.1 1454.871326.088 1469.34
#Mann= 8 ,-1 , 0
       0      .1       0     290     .06       0     350      .1       0
  583.25     .06       0  668.63    .045       0  691.71      .1       0
 1060.88     .04       0 1290.88      .1       0
#XS Ineff= 2 , 0
                          744.13         1448.23
Permanent Ineff=
       F       T
Bank Sta=668.63,691.71
XS Rating Curve= 0 ,0
Exp/Cntr(USF)=0,0
Exp/Cntr=0.3,0.1

Type RM Length L Ch R = 1 ,132     ,,,
XS GIS Cut Line= 4
2036242.59273598222514.3587500452036502.58082375222811.769365624
2036980.43995821222857.2406944782037351.53370818222590.313611135
#Sta/Elev= 30
       0 1476.52    41.7 1475.64    48.5 1472.69    64.8 1461.61    92.7 1460.81
   106.6 1452.15   111.3 1450.87   205.9 1447.56   225.8 1448.53   255.2 1445.22
   271.7 1447.79     295  1447.9   304.3  1445.8   320.5 1438.82   327.5 1438.23
   863.2 1438.81   930.9 1439.17   987.1 1444.01  1020.8 1443.75  1068.6 1446.39
  1099.5 1445.95  1132.1 1449.36  1153.2 1449.99  1175.7 1454.68  1202.6 1454.68
  1217.5 1453.03  1262.4  1453.3  1284.9 1455.72  1313.1  1463.21332.167 1466.96
#Mann= 10 ,-1 , 0
       0     .04       0     110     .06       0     130      .1       0
     260    .025       0   320.5    .045       0   863.2    .025       0
  965.05      .1       0 1025.05     .12       0 1135.05     .04       0
 1305.05      .1       0
Bank Sta=320.5,863.2
XS Rating Curve= 0 ,0
Exp/Cntr(USF)=0,0
Exp/Cntr=0.3,0.1
LCMann Table=0

Chan Stop Cuts=-1
Use User Specified Reach Order=0
Composite Channel Slope=5